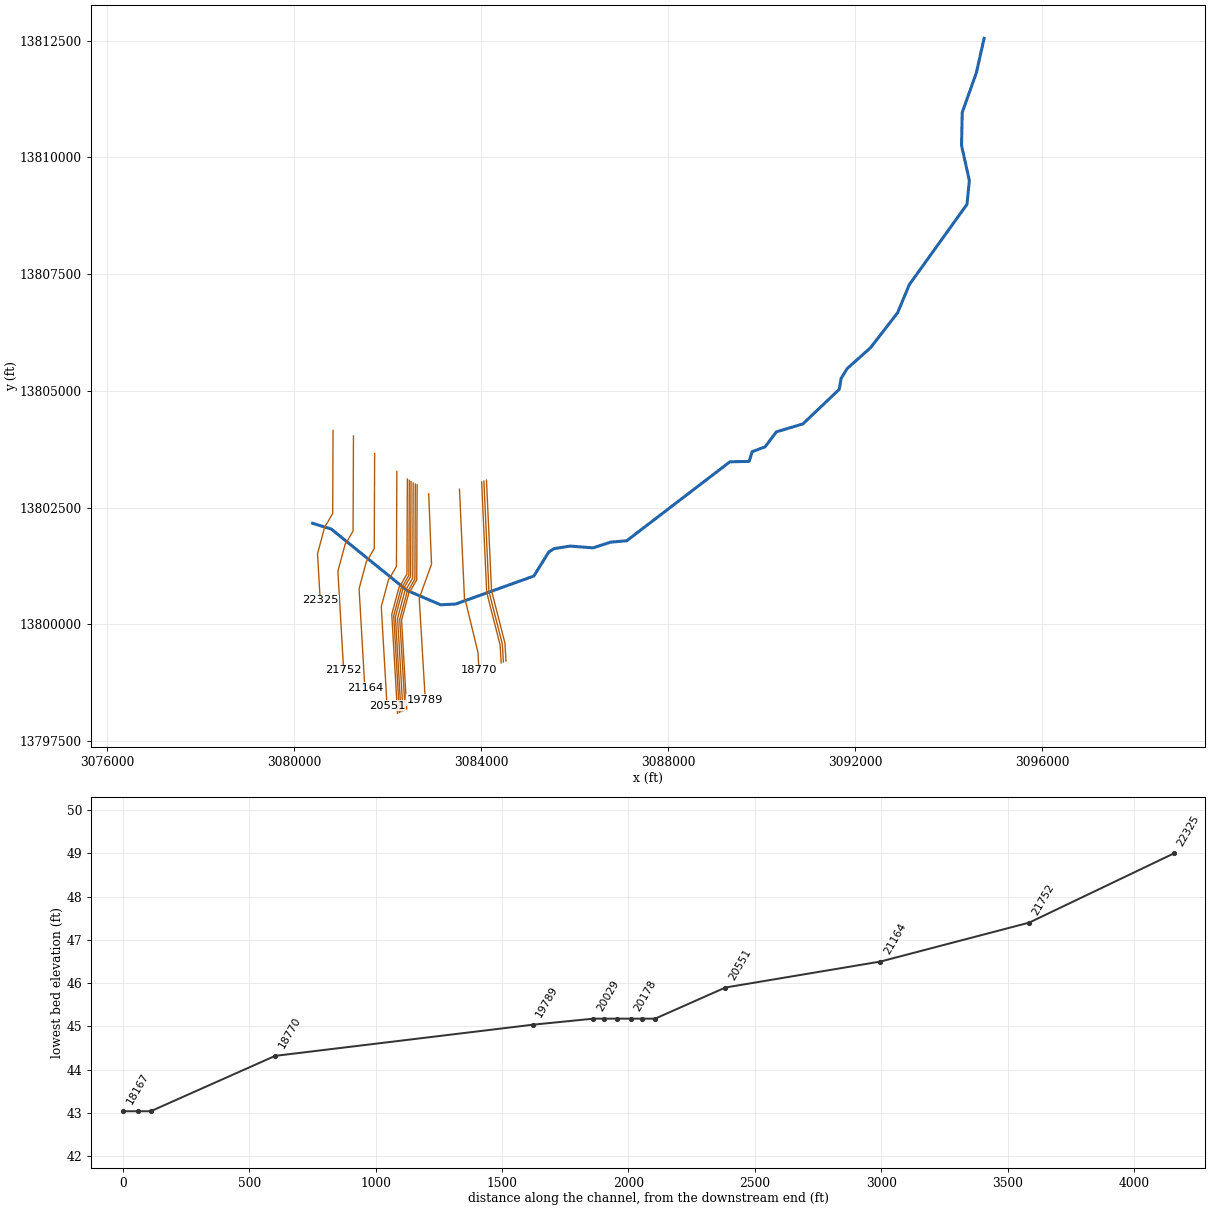
--- D112-00-00.prj (project) ---

Proj Title=D112-00-00
Current Plan=p02
Default Exp/Contr=.3,.1
English Units
Geom File=g05
Flow File=f01
Flow File=f06
Flow File=f04
Plan File=p06
Plan File=p02
Plan File=p04
Y Axis Title=Elevation
X Axis Title(PF)=Main Channel Distance
X Axis Title(XS)=Station
BEGIN DESCRIPTION:
Brays Bayou Watershed
Willow Waterhole Bayou
HCFCD Unit D112-00-00
Flood Hazard & Floodway Model
10, 2, 1, 0.2% Event
Filename D112.prj
Prepared by: Dodson & Associates, Inc.   Date: September 2003
Reviewed by:____________________	 Date:_________
STATUS (Final RAS, SVSQ)
FOR FLOOD HARZARD RECOVERY DATA ONLY,03/02/2004
Will Be Voided Upon Release of The Preliminary DFIRM
END DESCRIPTION:
DSS File=dss
DSS Export Rating Curves= 0
DSS Export Rating Curve Sorted= 0
DSS Export Volume Flow Curves= 0
DXF OffsetX= 0
DXF OffsetY= 0
DXF ScaleX= 1
DXF ScaleY= 10

--- D112-00-00.p02 (plan) ---

Plan Title=Floodway
Version=Version 3.0.1  Mar 2001
Short Identifier=Floodway0607
Geom File=g05
Flow File=f06
Subcritical Flow
K Sum by GR= 0
Std Step Tol= 0.01
Critical Tol= 0.01
Num of Std Step Trials= 20
Max Error Tol= 0.3
Flow Tol Ratio= 0.001
Split Flow NTrial= 30
Split Flow Tol= 0.02
Split Flow Ratio= 0.02
Log Output Level= 0
Friction Slope Method= 1
Unsteady Friction Slope Method= 2
Parabolic Critical Depth
Global Vel Dist= 0 , 0 , 0
Global Log Level= 0
CheckData=True
Encroach Param=-1 ,0,0, 2
Encroach River=D112-00-00
Encroach Reach=D112-00-00
Encroach Node=22325
       1    2046    2097
Encroach Node=21752
       1    2267    2328
Encroach Node=21164
       1    2275    2331
Encroach Node=20551
       1    2282    2340
Encroach Node=20273
       1    2264 2363.62
Encroach Node=20223
       1 2286.34 2361.57
Encroach Node=20201
       1 2273.04 2361.57
Encroach Node=20178
       1 2273.04 2346.86
Encroach Node=20123
       1 2274.86 2349.57
Encroach Node=20097
       1 2274.86 2363.62
Encroach Node=20071
       1 2282.55 2363.62
Encroach Node=20029
       1 2280.36    2369
Encroach Node=19789
       1 2198.64  2278.1
Encroach Node=18770
       1 2365.11 2445.34
Encroach Node=18277
       1 2348.18 2424.29
Encroach Node=18226
       1 2353.02 2425.98
Encroach Node=18197
       1 2353.02 2431.98
Encroach Node=18167
       1 2359.02 2431.98
Encroach Node=18125
       1 2349.84 2431.98
Encroach Node=17727
       1 2242.06 2305.74
Encroach Node=17323
       1 2140.93  2207.5
Encroach Node=16410
       1 1620.84 1708.37
Encroach Node=16158
       1 1998.96 2127.86
Encroach Node=16106
       1 2039.68 2130.68
Encroach Node=16082
       1 2039.68 2150.27
Encroach Node=16057
       1 2064.51 2150.27
Encroach Node=15937
       1 2112.85 2203.78
Encroach Node=15913
       1 2112.85 2235.58
Encroach Node=15888
       1 2147.85 2235.58
Encroach Node=15814
       1 2160.85 2248.58
Encroach Node=15667
       1 2283.82 2373.28
Encroach Node=14972
       1  1984.3 2070.79
Encroach Node=13959
       1 1622.02 1698.17
Encroach Node=12971
       1 1480.36 1592.97
Encroach Node=12115
       1 1475.39 1567.03
Encroach Node=10751
       1 1869.22  1968.7
Encroach Node=10059
       1 2250.68 2376.46
Encroach Node=9723
       1  2548.3 2676.98
Encroach Node=9642
       1 2561.23 2703.18
Encroach Node=9564
       1 2561.23 2703.18
Encroach Node=9486
       1 2563.13 2681.97
Encroach Node=9421
       1 2562.08 2667.69
Encroach Node=7801
       1 2408.11 2486.02
Encroach Node=7728
       1 2410.61 2491.76
Encroach Node=7704
       1 2410.61 2495.79
Encroach Node=7680
       1 2417.88 2495.79
Encroach Node=7649
       1 2411.96  2497.5
Encroach Node=7625
       1  2404.6  2497.5
Encroach Node=7601
       1  2404.6 2487.42
Encroach Node=7534
       1 2412.27 2490.18
Encroach Node=7144
       1 2389.05 2500.02
Encroach Node=5973
       1 1880.87 1988.04
Encroach Node=5893
       1 1882.49 1989.66
Encroach Node=5872
       1 1882.49 1991.23
Encroach Node=5850
       1 1884.06 1991.23
Encroach Node=5821
       1 1880.55 1987.72
Encroach Node=5354
       1 1929.08 2021.08
Encroach Node=4828
       1 2095.84 2193.31
Encroach Node=4468
       1 1987.77  2081.8
Encroach Node=3922
       1 1977.53 2077.28
Encroach Node=3845
       1 1989.74 2089.49
Encroach Node=3796
       1 1989.74 2097.49
Encroach Node=3746
       1 1990.65 2097.49
Encroach Node=3609
       1 1967.42 2067.17
Encroach Node=2955
       1 1566.39 1670.36
Encroach Node=1723
       1   906.9 1027.79
Encroach Node=1669
       1  922.84 1058.17
Encroach Node=1508
       1  922.84 1150.37
Encroach Node=1346
       1 1048.21 1150.37
Encroach Node=1304
       1 1048.21 1150.37
Encroach Node=679
       1  528.72   601.8
Encroach Reach=D112-00-00_0007
Encroach Node=22325
       1    2046    2097
Encroach Node=21752
       1    2267    2328
Encroach Node=21164
       1    2275    2331
Encroach Node=20551
       1    2282    2340
Encroach Node=20273
       1    2264 2363.62
Encroach Node=20223
       1 2286.34 2361.57
Encroach Node=20201
       1 2273.04 2361.57
Encroach Node=20178
       1 2273.04 2346.86
Encroach Node=20123
       1 2274.86 2349.57
Encroach Node=20097
       1 2274.86 2363.62
Encroach Node=20071
       1 2282.55 2363.62
Encroach Node=20029
       1 2280.36    2369
Encroach Node=19789
       1 2198.64  2278.1
Encroach Node=18770
       1 2365.11 2445.34
Encroach Node=18277
       1 2348.18 2424.29
Encroach Node=18226
       1 2353.02 2425.98
Encroach Node=18197
       1 2353.02 2431.98
Encroach Node=18167
       1 2359.02 2431.98
Encroach Node=18125
       1 2349.84 2431.98
Encroach Node=17727
       1 2242.06 2305.74
Encroach Node=17323
       1 2140.93  2207.5
Encroach Node=16410
       1 1620.84 1708.37
Encroach Node=16158
       1 1998.96 2127.86
Encroach Node=16106
       1 2039.68 2130.68
Encroach Node=16082
       1 2039.68 2150.27
Encroach Node=16057
       1 2064.51 2150.27
Encroach Node=15937
       1 2112.85 2203.78
Encroach Node=15913
       1 2112.85 2235.58
Encroach Node=15888
       1 2147.85 2235.58
Encroach Node=15814
       1 2160.85 2248.58
Encroach Node=15667
       1 2283.82 2373.28
Encroach Node=14972
       1  1984.3 2070.79
Encroach Node=13959
       1 1622.02 1698.17
Encroach Node=12971
       1 1480.36 1592.97
Encroach Node=12115
       1 1475.39 1567.03
Encroach Node=10751
       1 1869.22  1968.7
Encroach Node=10059
       1 2250.68 2376.46
Encroach Node=9723
       1  2548.3 2676.98
Encroach Node=9642
       1 2561.23 2703.18
Encroach Node=9564
       1 2561.23 2703.18
Encroach Node=9486
       1 2563.13 2681.97
Encroach Node=9421
       1 2562.08 2667.69
Encroach Node=7801
       1 2408.11 2486.02
Encroach Node=7728
       1 2410.61 2491.76
Encroach Node=7704
       1 2410.61 2495.79
Encroach Node=7680
       1 2417.88 2495.79
Encroach Node=7649
       1 2411.96  2497.5
Encroach Node=7625
       1  2404.6  2497.5
Encroach Node=7601
       1  2404.6 2487.42
Encroach Node=7534
       1 2412.27 2490.18
Encroach Node=7144
       1 2389.05 2500.02
Encroach Node=5973
       1 1880.87 1988.04
Encroach Node=5893
       1 1882.49 1989.66
Encroach Node=5872
       1 1882.49 1991.23
Encroach Node=5850
       1 1884.06 1991.23
Encroach Node=5821
       1 1880.55 1987.72
Encroach Node=5354
       1 1929.08 2021.08
Encroach Node=4828
       1 2095.84 2193.31
Encroach Node=4468
       1 1987.77  2081.8
Encroach Node=3922
       1 1977.53 2077.28
Encroach Node=3845
       1 1989.74 2089.49
Encroach Node=3796
       1 1989.74 2097.49
Encroach Node=3746
       1 1990.65 2097.49
Encroach Node=3609
       1 1967.42 2067.17
Encroach Node=2955
       1 1566.39 1670.36
Encroach Node=1723
       1   906.9 1027.79
Encroach Node=1669
       1  922.84 1058.17
Encroach Node=1508
       1  922.84 1150.37
Encroach Node=1346
       1 1048.21 1150.37
Encroach Node=1304
       1 1048.21 1150.37
Encroach Node=679
       1  528.72   601.8
Computation Interval=1HOUR
Output Interval=1HOUR
Run HTab= 0
Run UNet= 0
Run PostProcess= 0
UNET Theta= 1
UNET ZTol= 0.02
UNET ZSATol= 0.1
UNET MxIter= 20
UNET MaxInSteps= 20
UNET DtIC= 0
UNET DtMin= 0
UNET MaxCRTS= 20
UNET WFStab= 2
UNET SFStab= 1
UNET WFX= 1
UNET SFX= 1
UNET Convert EG Bridges=-1
UNET Use Existing IB Tables=-1
Instantaneous Interval=1HOUR
Write IC File= 0
Write Velocity= 0
Write Detailed= 0

--- D112-00-00.p01 (plan) ---

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Plan Title=Plan 01
Short Identifier=SV-SQ
Geom File=g05
Flow File=f01
Encroach Param=-1 ,0,0, 0

--- D112-00-00.p04 (plan) ---

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Plan Title=Storage Routing
Short Identifier=Store_Rout
Geom File=g05
Flow File=f04
Encroach Param=-1 ,0,0, 0

--- D112-00-00.p06 (plan) ---

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Plan Title=FEMA Effective June 2007
Short Identifier=FEMAeff0607
Geom File=g05
Flow File=f01
Encroach Param=-1 ,0,0, 0
DSS File=dss

--- D112-00-00.f06 (steady flow) ---

Flow Title=Floodway
Version=Version 3.0.1  Mar 2001
Number of Profiles= 2
Profile Names=1PCT_100yr,1PCTFloodway_100yrFW
River Rch & RM=D112-00-00,D112-00-00_0007 ,22325
    1033    1033
River Rch & RM=D112-00-00,D112-00-00_0007 ,21752
    1182    1182
River Rch & RM=D112-00-00,D112-00-00_0007 ,21164
    1360    1360
River Rch & RM=D112-00-00,D112-00-00_0007 ,20551
    1533    1533
River Rch & RM=D112-00-00,D112-00-00_0007 ,20029
    1565    1565
River Rch & RM=D112-00-00,D112-00-00_0007 ,18125
    1565    1565
River Rch & RM=D112-00-00,D112-00-00_0007 ,15814
    1730    1730
River Rch & RM=D112-00-00,D112-00-00_0007 ,14972
    1981    1981
River Rch & RM=D112-00-00,D112-00-00_0007 ,13959
    2261    2261
River Rch & RM=D112-00-00,D112-00-00_0007 ,12971
    2536    2536
River Rch & RM=D112-00-00,D112-00-00_0007 ,12115
    3041    3041
River Rch & RM=D112-00-00,D112-00-00_0007 ,10751
    3628    3628
River Rch & RM=D112-00-00,D112-00-00_0007 ,9421
    4001    4001
River Rch & RM=D112-00-00,D112-00-00_0007 ,7144
    4321    4321
River Rch & RM=D112-00-00,D112-00-00_0007 ,5354
    4595    4595
River Rch & RM=D112-00-00,D112-00-00_0007 ,3922
    5050    5050
River Rch & RM=D112-00-00,D112-00-00_0007 ,1723
    5438    5438
Boundary for River Rch & Prof#=D112-00-00,D112-00-00_0007 , 1
Up Type= 0
Dn Type= 1
Dn Known WS=46.44
Boundary for River Rch & Prof#=D112-00-00,D112-00-00_0007 , 2
Up Type= 0
Dn Type= 1
Dn Known WS=46.44
DSS Import GetInterval= 0
DSS Import GetPeak= 0
DSS Import FillOption= 0

--- D112-00-00.f01 (steady flow) ---

Flow Title=FEMA Effective June 2007
Version=Version 3.0.1  Mar 2001
Number of Profiles= 4
Profile Names=10PCT_10yr,2PCT_50yr,1PCT_100yr,0.2PCT_500yr
River Rch & RM=D112-00-00,D112-00-00_0007 ,22325
      35     843    1033    1344
River Rch & RM=D112-00-00,D112-00-00_0007 ,21752
      95     962    1182    1578
River Rch & RM=D112-00-00,D112-00-00_0007 ,21164
     271    1103    1360    1865
River Rch & RM=D112-00-00,D112-00-00_0007 ,20551
     663    1240    1533    2151
River Rch & RM=D112-00-00,D112-00-00_0007 ,20029
    1027    1400    1565    2151
River Rch & RM=D112-00-00,D112-00-00_0007 ,18125
    1099    1400    1565    2020
River Rch & RM=D112-00-00,D112-00-00_0007 ,15814
    1199    1536    1730    2147
River Rch & RM=D112-00-00,D112-00-00_0007 ,14972
    1330    1761    1981    2464
River Rch & RM=D112-00-00,D112-00-00_0007 ,13959
    1473    2014    2261    2819
River Rch & RM=D112-00-00,D112-00-00_0007 ,12971
    1609    2262    2536    3168
River Rch & RM=D112-00-00,D112-00-00_0007 ,12115
    1886    2700    3041    3793
River Rch & RM=D112-00-00,D112-00-00_0007 ,10751
    2201    3208    3628    4519
River Rch & RM=D112-00-00,D112-00-00_0007 ,9421
    2413    3531    4001    5013
River Rch & RM=D112-00-00,D112-00-00_0007 ,7144
    2593    3807    4321    5439
River Rch & RM=D112-00-00,D112-00-00_0007 ,5354
    2747    4044    4595    5806
River Rch & RM=D112-00-00,D112-00-00_0007 ,3922
    3002    4435    5050    6417
River Rch & RM=D112-00-00,D112-00-00_0007 ,1723
    3218    4769    5438    6941
Boundary for River Rch & Prof#=D112-00-00,D112-00-00_0007 , 1
Up Type= 0
Dn Type= 3
Dn Slope=.0006
Boundary for River Rch & Prof#=D112-00-00,D112-00-00_0007 , 2
Up Type= 0
Dn Type= 3
Dn Slope=.0006
Boundary for River Rch & Prof#=D112-00-00,D112-00-00_0007 , 3
Up Type= 0
Dn Type= 3
Dn Slope=.0006
Boundary for River Rch & Prof#=D112-00-00,D112-00-00_0007 , 4
Up Type= 0
Dn Type= 3
Dn Slope=.0006
DSS Import GetInterval= 0
DSS Import GetPeak= 0
DSS Import FillOption= 0

--- D112-00-00.f04 (steady flow) ---

Flow Title=Storage Routing
Version=Version 3.0.1  Mar 2001
Number of Profiles= 8
Profile Names=.1,.2,.4,.6,.8,1.0,1.2,1.5
River Rch & RM=D112-00-00,D112-00-00_0007 ,22325
     155     310     620     930    1240    1550    1860    2325
River Rch & RM=D112-00-00,D112-00-00_0007 ,20029
     156     312     624     936    1248    1560    1872    2340
River Rch & RM=D112-00-00,D112-00-00_0007 ,18125
     153     306     612     918    1224    1530    1836    2295
River Rch & RM=D112-00-00,D112-00-00_0007 ,15814
     252     504    1008    1512    2016    2520    3024    3780
River Rch & RM=D112-00-00,D112-00-00_0007 ,12115
     362     724    1448    2172    2896    3620    4344    5430
River Rch & RM=D112-00-00,D112-00-00_0007 ,9421
     543    1086    2172    3258    4344    5430    6516    8145
Boundary for River Rch & Prof#=D112-00-00,D112-00-00_0007 , 1
Up Type= 0
Dn Type= 3
Dn Slope=.0006
Boundary for River Rch & Prof#=D112-00-00,D112-00-00_0007 , 2
Up Type= 0
Dn Type= 3
Dn Slope=.0006
Boundary for River Rch & Prof#=D112-00-00,D112-00-00_0007 , 3
Up Type= 0
Dn Type= 3
Dn Slope=.0006
Boundary for River Rch & Prof#=D112-00-00,D112-00-00_0007 , 4
Up Type= 0
Dn Type= 3
Dn Slope=.0006
Boundary for River Rch & Prof#=D112-00-00,D112-00-00_0007 , 5
Up Type= 0
Dn Type= 3
Dn Slope=.0006
Boundary for River Rch & Prof#=D112-00-00,D112-00-00_0007 , 6
Up Type= 0
Dn Type= 3
Dn Slope=.0006
Boundary for River Rch & Prof#=D112-00-00,D112-00-00_0007 , 7
Up Type= 0
Dn Type= 3
Dn Slope=.0006
Boundary for River Rch & Prof#=D112-00-00,D112-00-00_0007 , 8
Up Type= 0
Dn Type= 3
Dn Slope=.0006
DSS Import GetInterval= 0
DSS Import GetPeak= 0
DSS Import FillOption= 0

--- D112-00-00.g05 (geometry) ---

Geom Title=D112-00-00 June 2007
Version=Version 3.0.1  Mar 2001

River Reach=D112-00-00      ,D112-00-00_0007
Reach XY= 30
     3080395.471    13802165.174     3080794.689    13802042.537
     3082414.068    13800729.186      3083135.29    13800420.365
      3083455.03    13800436.853     3085129.683    13801035.823
     3085449.298    13801552.103     3085561.109    13801621.946
     3085904.452    13801678.097     3086393.755    13801639.253
     3086772.171     13801761.29     3087116.834    13801791.879
     3089325.117    13803482.054     3089735.048    13803490.379
      3089801.24     13803698.84        3090078.    13803802.821
     3090317.976    13804122.768     3090886.264    13804293.045
     3091664.084    13805033.589     3091703.378    13805266.295
     3091833.518    13805478.054       3092332.5    13805922.847
     3092913.143    13806674.316     3093164.196    13807276.779
     3094396.508    13808993.546     3094447.201      13809502.5
     3094280.081    13810256.284      3094294.98     13810961.91
     3094597.451    13811810.526     3094763.144      13812547.5

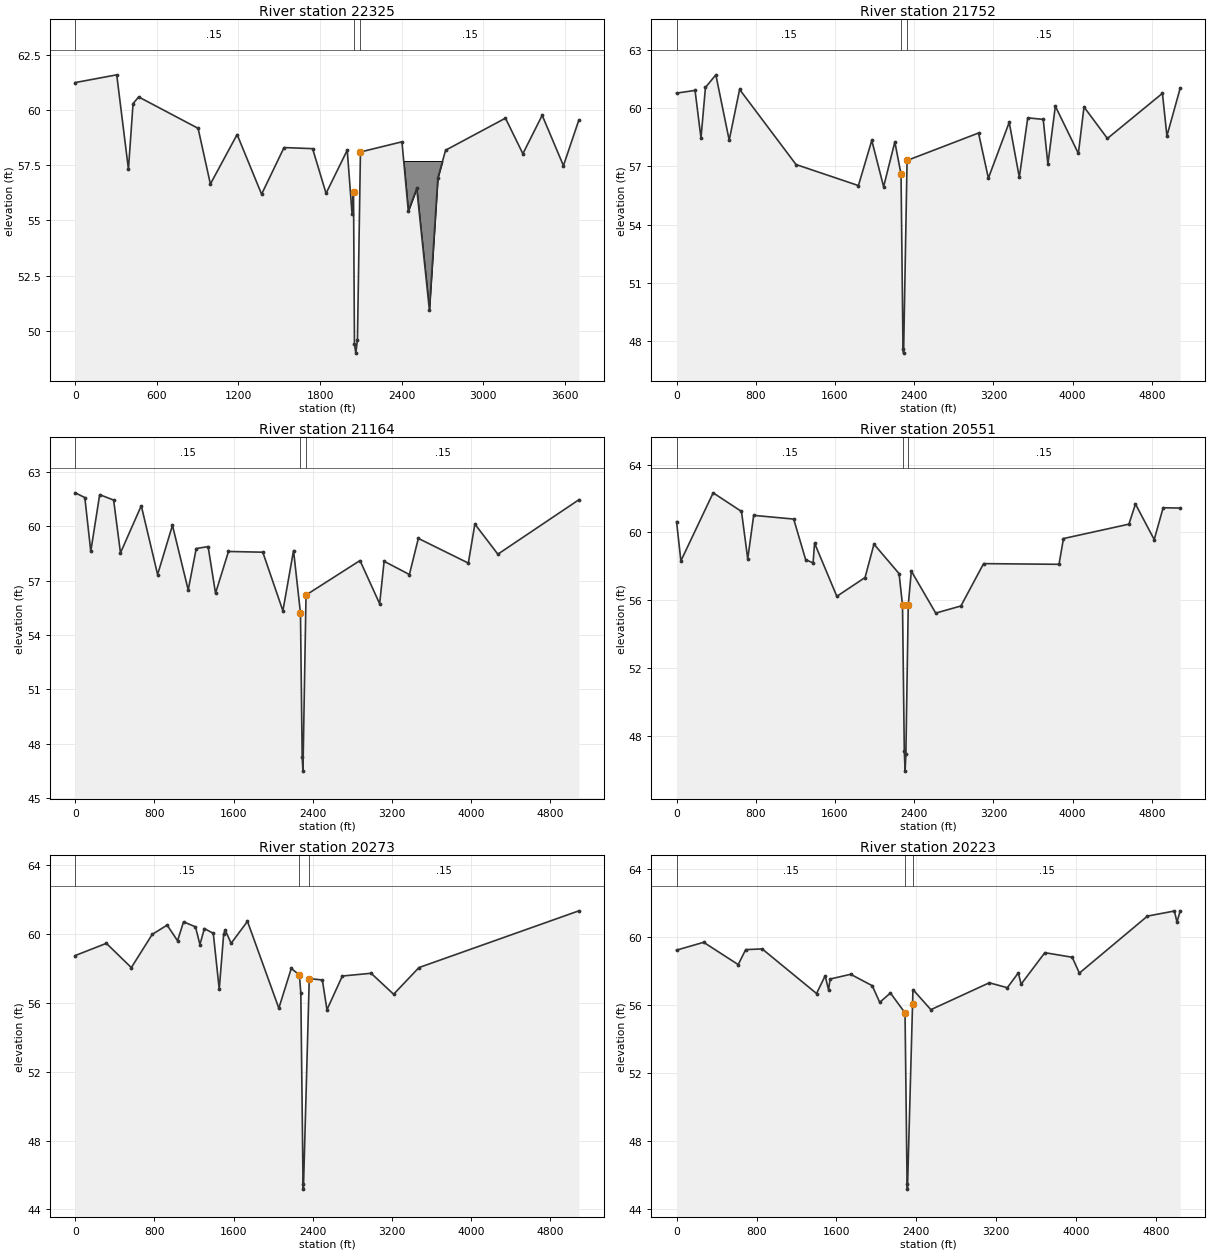
Type RM Length L Ch R = 1 ,22325   ,574.94,572.42,572.74
BEGIN DESCRIPTION:
22324.82-- Used Channel Survey from DAI 1997 report
END DESCRIPTION:
XS GIS Cut Line= 6
     3080833.104    13804152.689     3080825.641    13802375.782
     3080711.578    13802177.522     3080656.021    13802092.088
     3080501.051    13801513.052 3080558.667932813800518.6684026
#Sta/Elev= 30
       0   61.24  305.19   61.59  391.23   57.32  425.19   60.29  466.55   60.59
  903.39   59.17  993.77   56.65  1190.2   58.89  1370.2   56.19  1535.2    58.3
  1745.2   58.25 1844.16   56.23 1999.91   58.18  2035.5   55.29    2046    56.3
    2053    49.4    2063      49    2075    49.6    2097    58.1 2402.17   58.56
 2448.75   55.43 2510.86   56.45 2603.79   50.96 2666.14   56.93 2723.07   58.18
 3163.29   59.63 3291.16   58.02 3433.19   59.76 3589.41   57.48 3703.03   59.55
#Mann= 3 , 0 , 0
       0     .15       0    2046     .04       0    2097     .15       0
#XS Ineff= 2 , 0
       0    1990            2145       0
Permanent Ineff=
       T       T
#Block Obstruct= 1 ,-1
 2403.15 2699.76   57.69
Bank Sta=2046,2097
XS Rating Curve= 0
Exp/Cntr=.3,.1

Type RM Length L Ch R = 1 ,21752   ,582.94,588.53,593.95
BEGIN DESCRIPTION:
21752.40--Used Channel Survey from DAI 1997 report
END DESCRIPTION:
XS GIS Cut Line= 6
     3081269.965    13804034.136     3081261.427    13802001.176
     3081147.364    13801802.916     3081091.807    13801717.483
     3080936.837    13801138.446     3081059.688    13799018.202
#Sta/Elev= 30
       0   60.76  186.64    60.9  246.64   58.45  291.64   61.05  396.64    61.7
  531.64   58.34  636.64   60.95 1206.65   57.09 1836.65   56.01 1971.65   58.33
 2090.98   55.95  2204.5   58.25    2267    56.6    2287    47.6    2293    47.4
    2328    57.3 3049.77   58.71 3149.19   56.39 3359.64   59.26 3461.64   56.43
 3546.85   59.49 3703.07   59.41  3750.3   57.11 3825.42   60.09 4058.13   57.66
 4114.94   60.05  4351.3   58.43 4907.23   60.75 4952.31   58.56 5086.83   61.02
#Mann= 3 , 0 , 0
       0     .15       0    2267     .04       0    2328     .15       0
#XS Ineff= 2 , 0
       0    2230            2363       0
Permanent Ineff=
       T       T
Bank Sta=2267,2328
XS Rating Curve= 0
Exp/Cntr=.3,.1

Type RM Length L Ch R = 1 ,21164   ,567.48,612.94,603.54
BEGIN DESCRIPTION:
21163.86--Used Channel Survey from DAI 1997 report
END DESCRIPTION:
XS GIS Cut Line= 6
     3081723.181    13803659.531     3081714.643    13801626.571
      3081600.58    13801428.311     3081545.023    13801342.877
     3081390.053    13800763.841     3081512.905    13798643.596
#Sta/Elev= 30
       0   61.83   97.03   61.57  157.03   58.61  247.03   61.73  387.98   61.43
  457.04   58.52  667.04   61.12  832.04   57.33  982.04   60.04 1141.15   56.48
 1222.04   58.76 1342.04   58.87 1417.04    56.3 1547.86    58.6 1894.32   58.56
 2097.43   55.33 2204.96   58.65    2275    55.2    2292    47.3    2300    46.5
    2331    56.2 2876.21    58.1 3074.56   55.72 3119.64   58.06 3375.06   57.33
 3465.21   59.32 3970.24   57.96 4036.17   60.11 4268.49   58.45 5086.83   61.45
#Mann= 3 , 0 , 0
       0     .15       0    2275     .04       0    2331     .15       0
#XS Ineff= 2 , 0
       0    2235            2365       0
Permanent Ineff=
       T       T
Bank Sta=2275,2331
XS Rating Curve= 0
Exp/Cntr=.3,.1

Type RM Length L Ch R = 1 ,20551   ,242.6,278.3,272.63
BEGIN DESCRIPTION:
20550.92--Used Channel Survey from DAI 1997 report
END DESCRIPTION:
XS GIS Cut Line= 6
     3082198.187    13803276.214     3082189.649    13801243.254
     3082075.586    13801044.994      3082020.03     13800959.56
     3081865.059    13800380.524     3081987.911    13798260.279
#Sta/Elev= 30
       0   60.63   43.71   58.31  369.58   62.33  655.79   61.23  718.72   58.43
  778.72      61 1183.01   60.78 1303.51   58.39 1378.73   58.19 1393.73   59.36
 1618.73   56.22 1903.73   57.33 1993.73    59.3 2247.28   57.56    2282    55.7
    2300    47.1    2308    45.9    2316    46.9    2340    55.7 2370.93   57.71
 2617.38   55.23 2871.81   55.65 3100.76   58.15 3862.56   58.11 3907.64   59.63
 4568.75   60.48  4634.6   61.67 4824.17   59.57 4914.32   61.45 5086.83   61.43
#Mann= 3 , 0 , 0
       0     .15       0    2282     .04       0    2340     .15       0
#XS Ineff= 2 , 0
       0    2240            2372       0
Permanent Ineff=
       T       T
Bank Sta=2282,2340
XS Rating Curve= 0
Exp/Cntr=.3,.1

Type RM Length L Ch R = 1 ,20273   ,45.17,50.09,49.96
BEGIN DESCRIPTION:
20272.61--u/s approach Hillcroft West bridge;  channel copied from 20071
END DESCRIPTION:
XS GIS Cut Line= 6
     3082422.673    13803111.963     3082414.135    13801079.003
     3082300.072    13800880.743     3082244.515     13800795.31
     3082089.545    13800216.273     3082212.396    13798096.029
#Sta/Elev= 30
       0   58.76  314.47   59.47  566.67   58.06  777.56   59.99   928.2   60.53
 1033.64   59.62 1093.89   60.72  1214.4   60.43 1259.47    59.4 1304.47   60.33
 1394.48   60.05 1454.48    56.8 1499.48   60.02 1514.48   60.25 1574.48   59.47
 1739.48   60.75 2056.31    55.7 2182.03   58.01    2264   57.63 2278.55   56.58
 2300.79   45.48 2304.79   45.18 2363.62   57.42 2495.93   57.34 2542.51   55.61
 2697.79   57.57 2988.34   57.73 3215.58   56.51 3471.22   58.06 5086.83   61.36
#Mann= 3 , 0 , 0
       0     .15       0    2264     .04       0 2363.62     .15       0
#XS Ineff= 2 , 0
       0    2260            2370       0
Permanent Ineff=
       T       T
Bank Sta=2264,2363.62
XS Rating Curve= 0
Exp/Cntr=.5,.3

Type RM Length L Ch R = 1 ,20223   ,39.75,44.08,43.97
BEGIN DESCRIPTION:
20222.52--u/s face Hillcroft West bridge;  channel copied from 20071
END DESCRIPTION:
XS GIS Cut Line= 6
     3082464.485    13803084.373     3082455.947    13801051.413
     3082341.884    13800853.153     3082286.327     13800767.72
     3082131.357    13800188.683     3082251.422    13798114.897
#Sta/Elev= 30
       0   59.23  271.03   59.69  616.88   58.38  691.88   59.26  856.88    59.3
 1400.78   56.68 1486.89   57.72 1521.29   56.89 1536.35   57.53 1741.89   57.81
 1958.13   57.14 2032.98   56.16 2140.15   56.71 2286.34   55.54 2306.79   45.48
 2310.79   45.18 2361.57   56.06 2365.62   56.91    2545   55.73 3129.49   57.31
  3309.8   57.02 3419.73   57.89 3448.13   57.23 3685.42   59.08 3959.43   58.81
    4031   57.88 4712.18   61.23 4982.04   61.53 5007.63   60.88 5040.29   61.54
#Mann= 3 , 0 , 0
       0     .15       0 2286.34     .04       0 2361.57     .15       0
#XS Ineff= 2 , 0
       0    2264            2359       0
Permanent Ineff=
       T       T
Bank Sta=2286.34,2361.57
XS Rating Curve= 0
Exp/Cntr=.5,.3

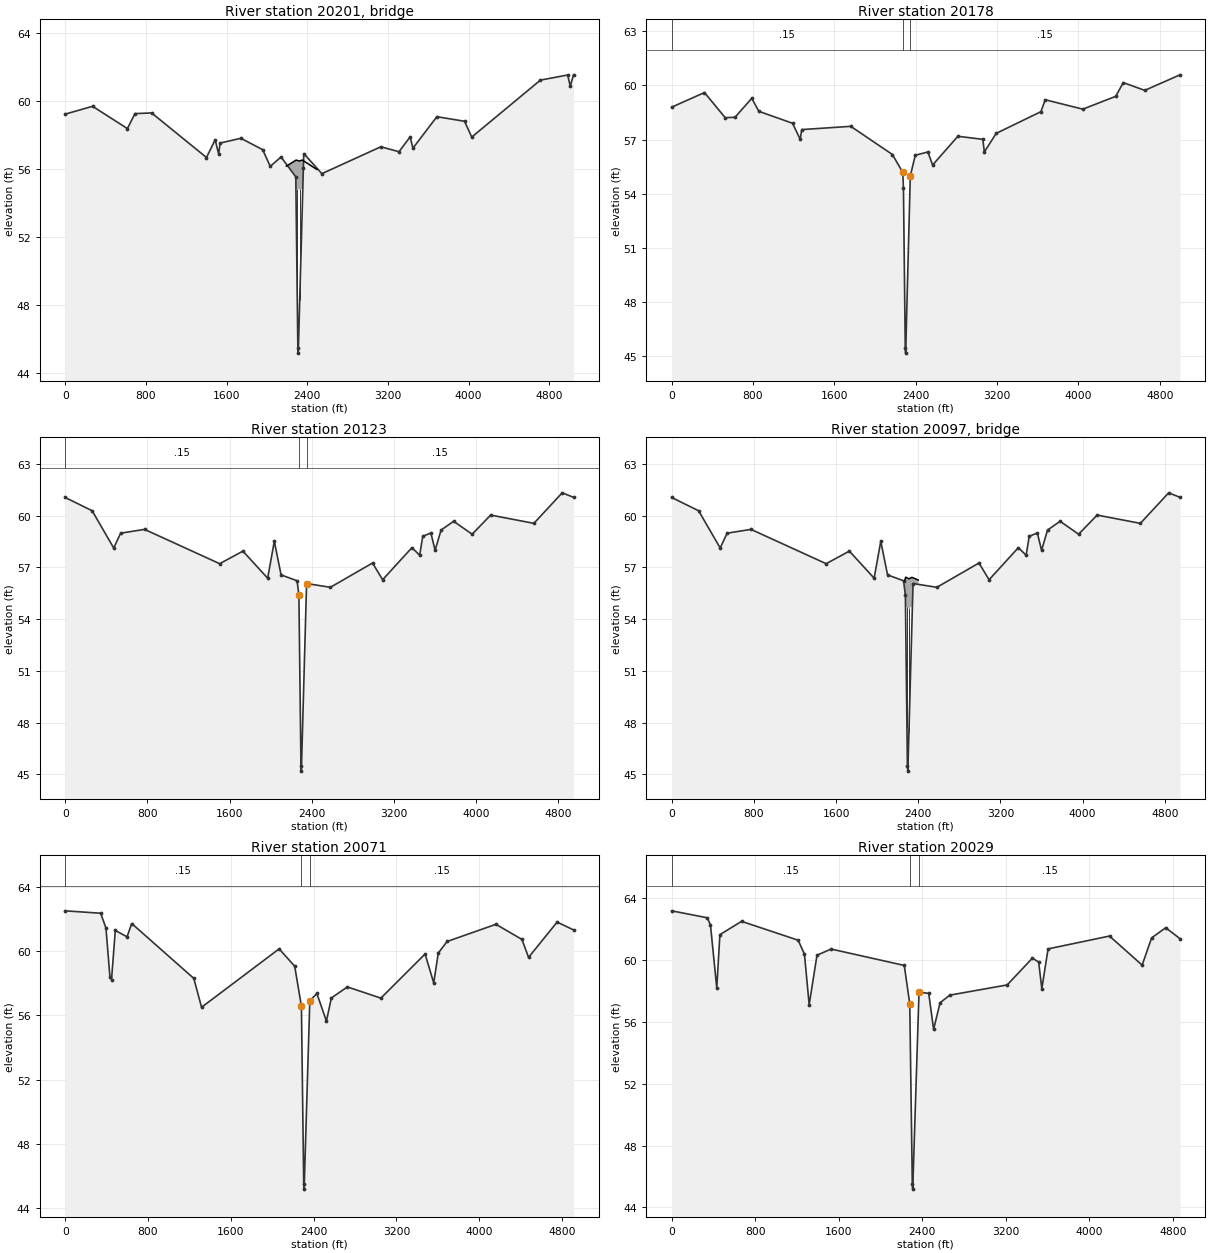
Type RM Length L Ch R = 3 ,20201   ,,,
BEGIN DESCRIPTION:
Hillcroft West (U) Bridge
END DESCRIPTION:
Bridge Culvert--1,0,-1,-1, 0
Deck Dist Width WeirC Skew NumUp NumDn MinLoCord MaxHiCord MaxSubmerge Is_Ogee
5,34,2.6,0, 7, 7, , , .95, 0, 0,0,,
 2192.51 2289.94 2289.94 2320.29 2350.63 2350.63 2494.89
   56.17   56.53   56.53   56.47   56.53   56.53   55.98
     -.2     -.2   54.85   54.79   54.85     -.2     -.2
 2183.01 2280.44 2280.44 2310.79 2341.13 2341.13 2485.39
   56.17   56.53   56.53   56.47   56.53   56.53   55.98
     -.2     -.2   54.85   54.79   54.85     -.2     -.2
Pier Skew, UpSta & Num, DnSta & Num=  ,2300.17, 2 ,2290.67, 2 , 0 , 0 , 0 ,,
    1.67    1.67
       0   54.85
    1.67    1.67
       0   54.85
Pier Skew, UpSta & Num, DnSta & Num=  ,2325.4, 2 ,2315.9, 2 , 0 , 0 , 0 ,,
    1.67    1.67
       0   54.85
    1.67    1.67
       0   54.85
BR Coef=-1 , 1 , 1 ,1.05, 0 ,,,.8,-1,1.2,0,
WSPro=,,,, 1 ,,,, 0 ,,,, 0 ,,,,-1 ,-1 ,-1 , 0 , 0 , 0 , 0 , 0
BC Design=,, 0 ,, 0 ,,,,,,

Type RM Length L Ch R = 1 ,20178   ,49.69,55.1,54.96
BEGIN DESCRIPTION:
20178.44--d/s face Hillcroft West bridge;  channel copied from 20071
END DESCRIPTION:
XS GIS Cut Line= 6
      3082501.28    13803060.103     3082492.742    13801027.143
     3082378.679    13800828.883     3082323.122     13800743.45
     3082168.152    13800164.413     3082285.763      13798131.5
#Sta/Elev= 30
       0   58.79  322.61    59.6  526.04   58.21  622.61   58.23  787.61   59.28
  857.43   58.56 1188.83    57.9 1264.14   57.01 1279.21   57.55 1761.24   57.73
 2171.01   56.17 2273.04   55.18 2279.46   54.31 2297.29   45.48 2301.29   45.18
 2346.86   54.98 2395.66   56.13 2519.56   56.31 2566.46   55.59 2814.91   57.18
 3060.11   57.01 3075.13   56.31 3191.48   57.34 3631.06   58.54  3674.4    59.2
 4043.68   58.68 4367.29   59.39 4441.38   60.15 4652.77   59.72 4999.34   60.58
#Mann= 3 , 0 , 0
       0     .15       0 2273.04     .04       0 2346.86     .15       0
#XS Ineff= 2 , 0
       0    2263            2355       0
Permanent Ineff=
       T       T
Bank Sta=2273.04,2346.86
XS Rating Curve= 0
Exp/Cntr=.5,.3

Type RM Length L Ch R = 1 ,20123   ,49.47,52.31,53.06
BEGIN DESCRIPTION:
20123.34--u/s face Hillcroft East bridge;  channel copied from 20071
END DESCRIPTION:
XS GIS Cut Line= 6
     3082547.273    13803029.753     3082538.735    13800996.793
     3082424.672    13800798.533     3082369.115      13800713.1
     3082214.145    13800134.063     3082328.692    13798152.255
#Sta/Elev= 30
       0   61.05  262.26   60.28  472.26   58.12  539.75   58.98  772.26    59.2
 1503.81   57.21 1729.76   57.94 1970.77   56.37 2035.45   58.51 2101.38   56.56
 2257.13   56.22 2274.86   55.39 2294.79   45.48 2298.79   45.18 2349.57   56.06
 2581.27   55.84 2991.36   57.25 3089.81   56.28 3374.87   58.14 3450.41    57.7
 3480.46    58.8 3559.53   58.99 3600.66   57.99 3658.95   59.16 3780.96   59.67
 3961.26   58.92 4141.56   60.03 4562.26   59.55 4837.89   61.32 4948.15   61.06
#Mann= 3 , 0 , 0
       0     .15       0 2274.86     .04       0 2349.57     .15       0
#XS Ineff= 2 , 0
       0    2262            2360       0
Permanent Ineff=
       T       T
Bank Sta=2274.86,2349.57
XS Rating Curve= 0
Exp/Cntr=.5,.3

Type RM Length L Ch R = 3 ,20097   ,,,
BEGIN DESCRIPTION:
Hillcroft East (D) Bridge
END DESCRIPTION:
Bridge Culvert--1,0,-1,-1, 0
Deck Dist Width WeirC Skew NumUp NumDn MinLoCord MaxHiCord MaxSubmerge Is_Ogee
9,34,2.6,0, 7, 7, , , .95, 0, 0,0,,
 2267.13 2278.36 2278.36 2308.29 2338.21 2338.21 2400.45
   56.22   56.43   56.43   56.33   56.42   56.42   56.26
     -.2     -.2   54.73   54.63   54.72     -.2     -.2
 2277.13 2287.36 2287.36 2317.79 2348.21 2348.21 2410.45
   56.22   56.43   56.43   56.33   56.42   56.42   56.26
     -.2     -.2   54.73   54.63   54.72     -.2     -.2
Pier Skew, UpSta & Num, DnSta & Num=  ,2290.31, 2 ,2300.31, 2 , 0 , 0 , 0 ,,
    1.67    1.67
       0   54.85
    1.67    1.67
       0   54.85
Pier Skew, UpSta & Num, DnSta & Num=  ,2309.26, 2 ,2319.26, 2 , 0 , 0 , 0 ,,
    1.67    1.67
       0   54.85
    1.67    1.67
       0   54.85
BR Coef=-1 , 1 , 1 ,1.05, 0 ,,,.8,-1,1.2,0,
WSPro=,,,, 1 ,,,, 0 ,,,, 0 ,,,,-1 ,-1 ,-1 , 0 , 0 , 0 , 0 , 0
BC Design=,, 0 ,, 0 ,,,,,,

Type RM Length L Ch R = 1 ,20071   ,42.52,42.49,42.27
BEGIN DESCRIPTION:
20071.03--d/s face Hillcroft East bridge; surveyed channel
END DESCRIPTION:
XS GIS Cut Line= 6
     3082593.083    13803005.126     3082584.545    13800972.166
     3082470.482    13800773.906     3082414.925    13800688.472
     3082259.955    13800109.436     3082376.688    13798163.885
#Sta/Elev= 30
       0   62.52  342.63   62.37   393.7   61.45  432.63   58.37  447.63   58.24
  484.08    61.3  597.63    60.9  642.63   61.73 1242.64   58.31 1317.64   56.51
 2067.16   60.15 2217.56   59.07 2282.55   56.58 2304.79   45.48 2308.79   45.18
 2363.62   56.91 2431.91   57.37 2524.12   55.65 2571.66   57.09 2726.94   57.78
 3050.12   57.08 3477.62   59.83 3561.04   58.03  3605.2   59.89 3690.26   60.61
 4162.12   61.68 4413.26   60.74 4477.69   59.62 4753.49   61.82 4912.08   61.33
#Mann= 3 , 0 , 0
       0     .15       0 2282.55     .04       0 2363.62     .15       0
#XS Ineff= 2 , 0
       0    2265            2380       0
Permanent Ineff=
       T       T
Bank Sta=2282.55,2363.62
XS Rating Curve= 0
Exp/Cntr=.5,.3

Type RM Length L Ch R = 1 ,20029   ,245.5,239.97,285.03
BEGIN DESCRIPTION:
20028.55--d/s exit Hillcroft East bridge;  channel copied from 20071
END DESCRIPTION:
XS GIS Cut Line= 6
      3082632.48    13802989.353     3082623.942    13800956.393
     3082509.879    13800758.133     3082454.322      13800672.7
     3082299.352    13800093.663      3082409.14    13798191.149
#Sta/Elev= 30
       0   63.17  341.86   62.72  371.86   62.24  431.86   58.18  461.86   61.63
  669.69   62.49 1211.86   61.27 1271.86   60.37 1316.86    57.1 1391.87    60.3
 1526.87    60.7 2227.83   59.64 2280.36   57.16 2304.79   45.48 2308.79   45.18
    2369   57.92 2462.17   57.83 2508.75   55.51 2570.86   57.23 2664.03   57.72
 3213.34   58.38 3454.83   60.11 3515.11   59.86 3545.16   58.14 3605.26   60.71
  4193.5   61.54 4506.02   59.66 4596.91   61.42 4732.13   62.08 4868.71   61.37
#Mann= 3 , 0 , 0
       0     .15       0 2280.36     .04       0    2369     .15       0
#XS Ineff= 2 , 0
       0    2267            2375       0
Permanent Ineff=
       T       T
Bank Sta=2280.36,2369
XS Rating Curve= 0
Exp/Cntr=.3,.1

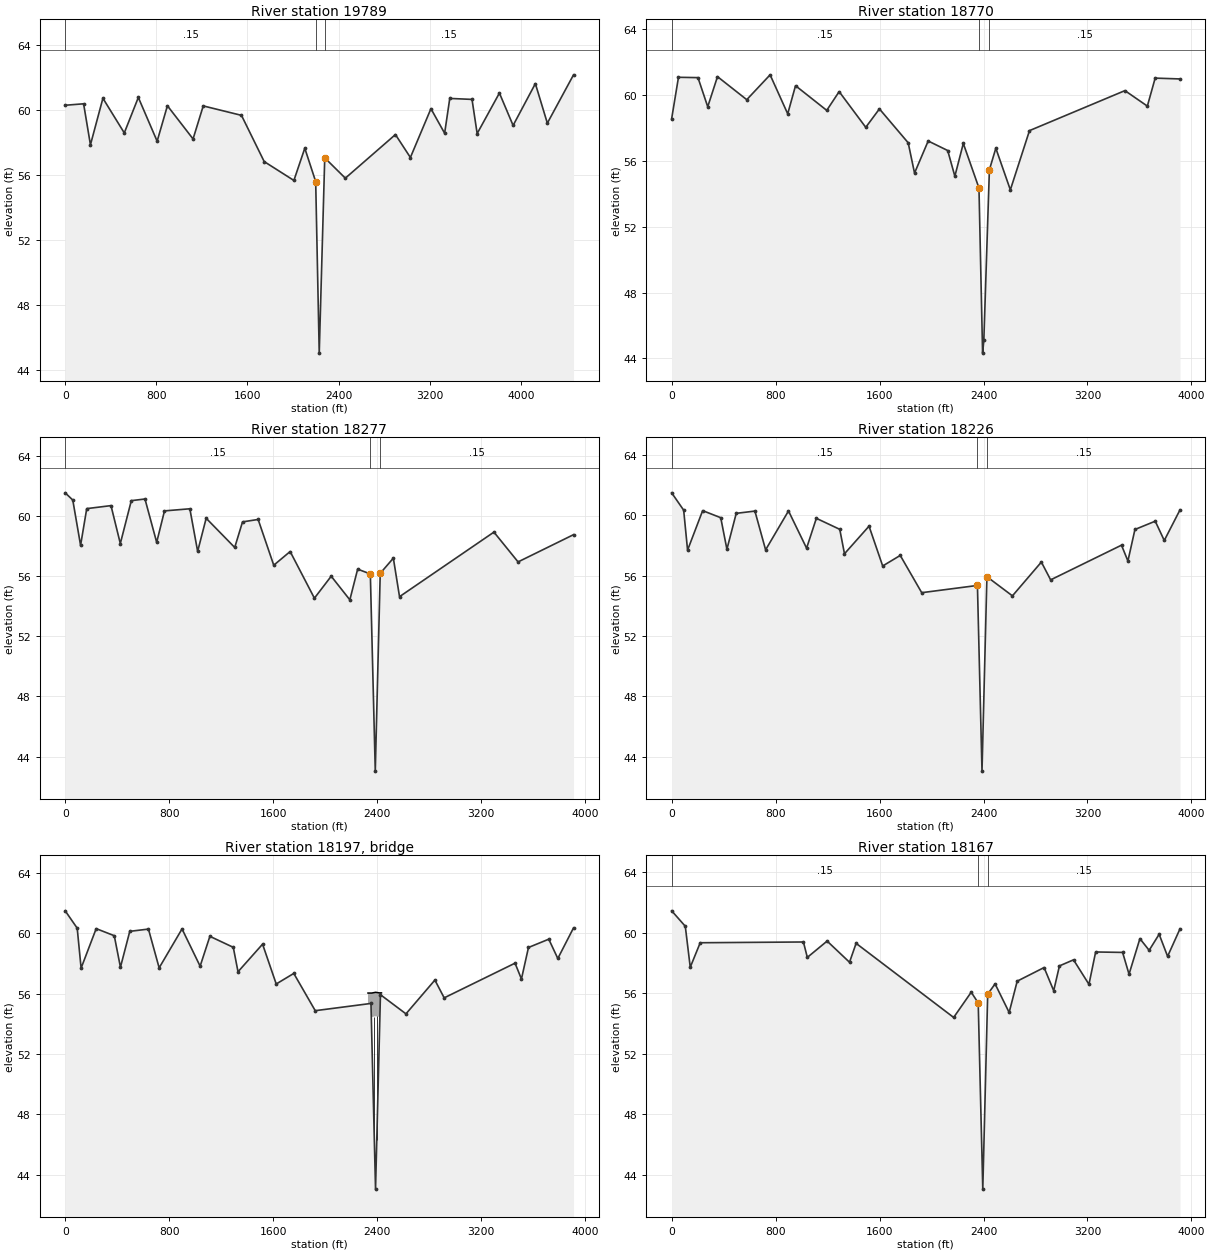
Type RM Length L Ch R = 1 ,19789   ,783.04,1018.76,1060.95
BEGIN DESCRIPTION:
 19788.57--surveyed channel
END DESCRIPTION:
XS GIS Cut Line= 5
     3082880.026     13802793.84     3082939.819    13801290.475
     3082711.276    13800656.277     3082676.812    13800563.015
     3082805.992    13798383.018
#Sta/Elev= 30
       0   60.27  161.47   60.36  221.52   57.84  330.92    60.7  518.61   58.57
  641.85   60.75  806.98   58.06  897.05   60.24 1122.23    58.2 1211.62   60.23
 1547.19   59.65 1746.61   56.81  2007.3   55.65 2102.97   57.63 2198.64   55.58
 2229.75   45.04  2278.1   57.04 2458.79   55.79 2898.68   58.47 3029.93   57.06
 3210.25   60.06 3330.46   58.55 3375.54   60.69 3570.88   60.63 3615.96   58.53
  3811.3   61.02 3931.51   59.03 4126.85    61.6 4232.04   59.17 4461.92   62.14
#Mann= 3 , 0 , 0
       0     .15       0 2198.64     .04       0  2278.1     .15       0
#XS Ineff= 2 , 0
       0    2168            2280       0
Permanent Ineff=
       T       T
Bank Sta=2198.64,2278.1
XS Rating Curve= 0
Exp/Cntr=.3,.1

Type RM Length L Ch R = 1 ,18770   ,483.25,492.45,491.67
BEGIN DESCRIPTION:
 18769.81--surveyed channel
END DESCRIPTION:
XS GIS Cut Line= 5
     3083538.465    13802894.727     3083645.221    13800548.978
     3083677.572     13800457.36     3083933.578    13799403.488
     3083955.552    13799021.687
#Sta/Elev= 30
       0   58.57   52.28   61.08  202.44   61.06  277.51   59.29  352.59   61.12
  577.82   59.72   757.6   61.23  893.15   58.86  953.21   60.57 1193.46   59.07
 1288.99   60.21 1493.77   58.04 1598.88   59.16 1820.38    57.1 1869.16   55.26
 1974.27   57.21 2124.42   56.63 2179.43   55.07 2244.55   57.06 2365.11   54.35
 2392.98   44.32 2402.47   45.09 2445.34   55.46 2494.84   56.77 2606.61   54.24
 2753.92   57.84 3488.39   60.27 3661.06   59.33 3721.16   61.03 3912.29   60.98
#Mann= 3 , 0 , 0
       0     .15       0 2365.11     .04       0 2445.34     .15       0
#XS Ineff= 2 , 0
       0    2334            2450       0
Permanent Ineff=
       T       T
Bank Sta=2365.11,2445.34
XS Rating Curve= 0
Exp/Cntr=.3,.1

Type RM Length L Ch R = 1 ,18277   ,49.1,51.41,51.27
BEGIN DESCRIPTION:
18277.36--u/s approach Landsdowne bridge; channel copied from 18167
END DESCRIPTION:
XS GIS Cut Line= 5
     3084012.735    13803050.712     3084119.491    13800704.963
     3084139.914    13800610.417     3084407.848    13799559.473
     3084429.822    13799177.672
#Sta/Elev= 30
       0   61.53   58.27   61.05  118.33   58.04  165.62   60.48  352.32   60.68
  424.13   58.16  508.74   61.01  613.85   61.12  703.94   58.24     764   60.33
   959.2   60.47 1019.27   57.64 1084.78   59.84 1304.56    57.9 1364.62    59.6
 1484.75   59.76 1604.87   56.72 1731.07   57.63 1917.77   54.53 2047.03   55.99
 2190.48   54.42 2250.54   56.46 2348.18   56.14  2386.2   43.04 2424.29   56.18
 2525.31   57.19 2572.78   54.63  3299.3   58.92 3485.06   56.94  3911.9   58.75
#Mann= 3 , 0 , 0
       0     .15       0 2348.18     .04       0 2424.29     .15       0
#XS Ineff= 2 , 0
       0    2331            2430       0
Permanent Ineff=
       T       T
Bank Sta=2348.18,2424.29
XS Rating Curve= 0
Exp/Cntr=.5,.3

Type RM Length L Ch R = 1 ,18226   ,56.36,58.81,58.61
BEGIN DESCRIPTION:
18225.95--u/s face Landsdowne bridge; channel copied from 18167
END DESCRIPTION:
XS GIS Cut Line= 5
     3084060.735    13803069.712     3084167.491    13800723.963
     3084187.914    13800629.417     3084455.848    13799578.473
     3084477.822    13799196.672
#Sta/Elev= 30
       0   61.49   92.31   60.34  122.34   57.69  238.39   60.31   377.6   59.84
  425.09   57.75   496.9   60.13  640.52   60.28  722.96   57.71  899.03   60.29
 1038.29   57.82 1113.36    59.8 1293.55   59.07 1329.89   57.45 1518.78   59.28
 1623.89   56.64 1759.03   57.34  1924.2   54.87 2353.02   55.35  2388.2   43.04
 2425.98   55.93 2622.32   54.66 2844.97    56.9 2916.44   55.72 3461.72   58.02
 3511.06   56.97  3565.1   59.06 3721.38   59.61 3790.87   58.33  3911.9   60.36
#Mann= 3 , 0 , 0
       0     .15       0 2353.02     .04       0 2425.98     .15       0
#XS Ineff= 2 , 0
       0    2333            2430       0
Permanent Ineff=
       T       T
Bank Sta=2353.02,2425.98
XS Rating Curve= 0
Exp/Cntr=.5,.3

Type RM Length L Ch R = 3 ,18197   ,,,
BEGIN DESCRIPTION:
Landsdowne Bridge
END DESCRIPTION:
Bridge Culvert--1,0,-1,-1, 0
Deck Dist Width WeirC Skew NumUp NumDn MinLoCord MaxHiCord MaxSubmerge Is_Ogee
9,40,2.6,0, 7, 7, , , .95, 0, 0,0,,
    2330 2359.65 2359.65  2389.2 2417.74 2417.74    2434
   56.04   56.04   56.04   56.09   56.05   56.05   56.05
     -.2     -.2   54.45    54.5   54.46     -.2     -.2
    2336 2365.65 2365.65  2395.2 2423.74 2423.74    2440
   56.04   56.04   56.04   56.09   56.05   56.05   56.05
     -.2     -.2   54.45    54.5   54.46     -.2     -.2
Pier Skew, UpSta & Num, DnSta & Num=  ,2378.68, 2 ,2384.68, 2 , 0 , 0 , 0 ,,
    1.69    1.69
       0    54.6
    1.69    1.69
       0    54.6
Pier Skew, UpSta & Num, DnSta & Num=  ,2397.71, 2 ,2403.71, 2 , 0 , 0 , 0 ,,
    1.69    1.69
       0    54.6
    1.69    1.69
       0    54.6
BR Coef=-1 , 1 , 1 ,1.05, 0 ,,,.8,-1,1.2,0,
WSPro=,,,, 1 ,,,, 0 ,,,, 0 ,,,,-1 ,-1 ,-1 , 0 , 0 , 0 , 0 , 0
BC Design=,, 0 ,, 0 ,,,,,,

Type RM Length L Ch R = 1 ,18167   ,40.72,42.49,42.34
BEGIN DESCRIPTION:
18167.13--d/s face Landsdowne bridge; surveyed channel
END DESCRIPTION:
XS GIS Cut Line= 5
     3084115.891    13803090.314     3084222.648    13800744.564
      3084243.07    13800650.019     3084511.005    13799599.074
     3084532.978    13799217.273
#Sta/Elev= 30
       0   61.44  104.77   60.42  142.96   57.71  219.66   59.33 1013.86   59.38
 1043.89   58.36 1196.27   59.44 1368.62   58.04 1419.28   59.29 2170.06   54.39
  2305.2   56.06 2359.02   55.35  2394.2   43.04 2431.98   55.93 2488.78   56.61
 2597.14   54.72 2659.06   56.79  2865.9   57.69 2939.91   56.16 2984.14    57.8
  3092.5    58.2 3211.28   56.58 3262.77   58.72 3470.31   58.69 3519.66   57.25
 3603.41    59.6 3674.45   58.83 3751.41   59.89 3816.52   58.43  3911.9   60.25
#Mann= 3 , 0 , 0
       0     .15       0 2359.02     .04       0 2431.98     .15       0
#XS Ineff= 2 , 0
       0    2336            2435       0
Permanent Ineff=
       T       T
Bank Sta=2359.02,2431.98
XS Rating Curve= 0
Exp/Cntr=.5,.3