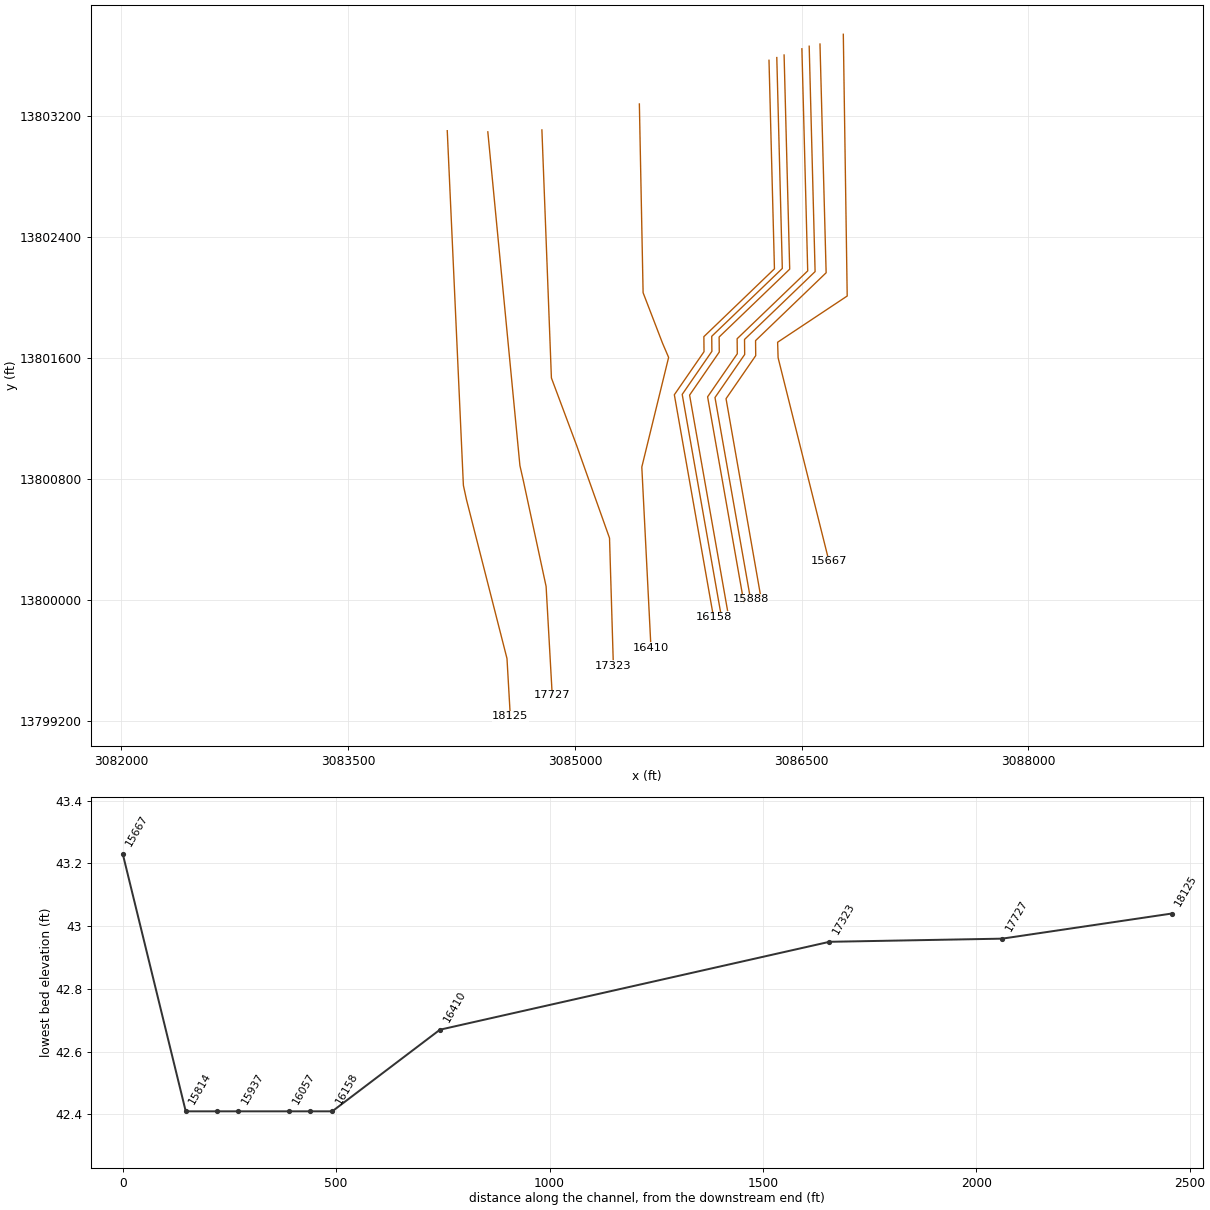
HEC-RAS study D112-00-00.prj: D112-00-00

--- D112-00-00.g05 (geometry) --- (continued)

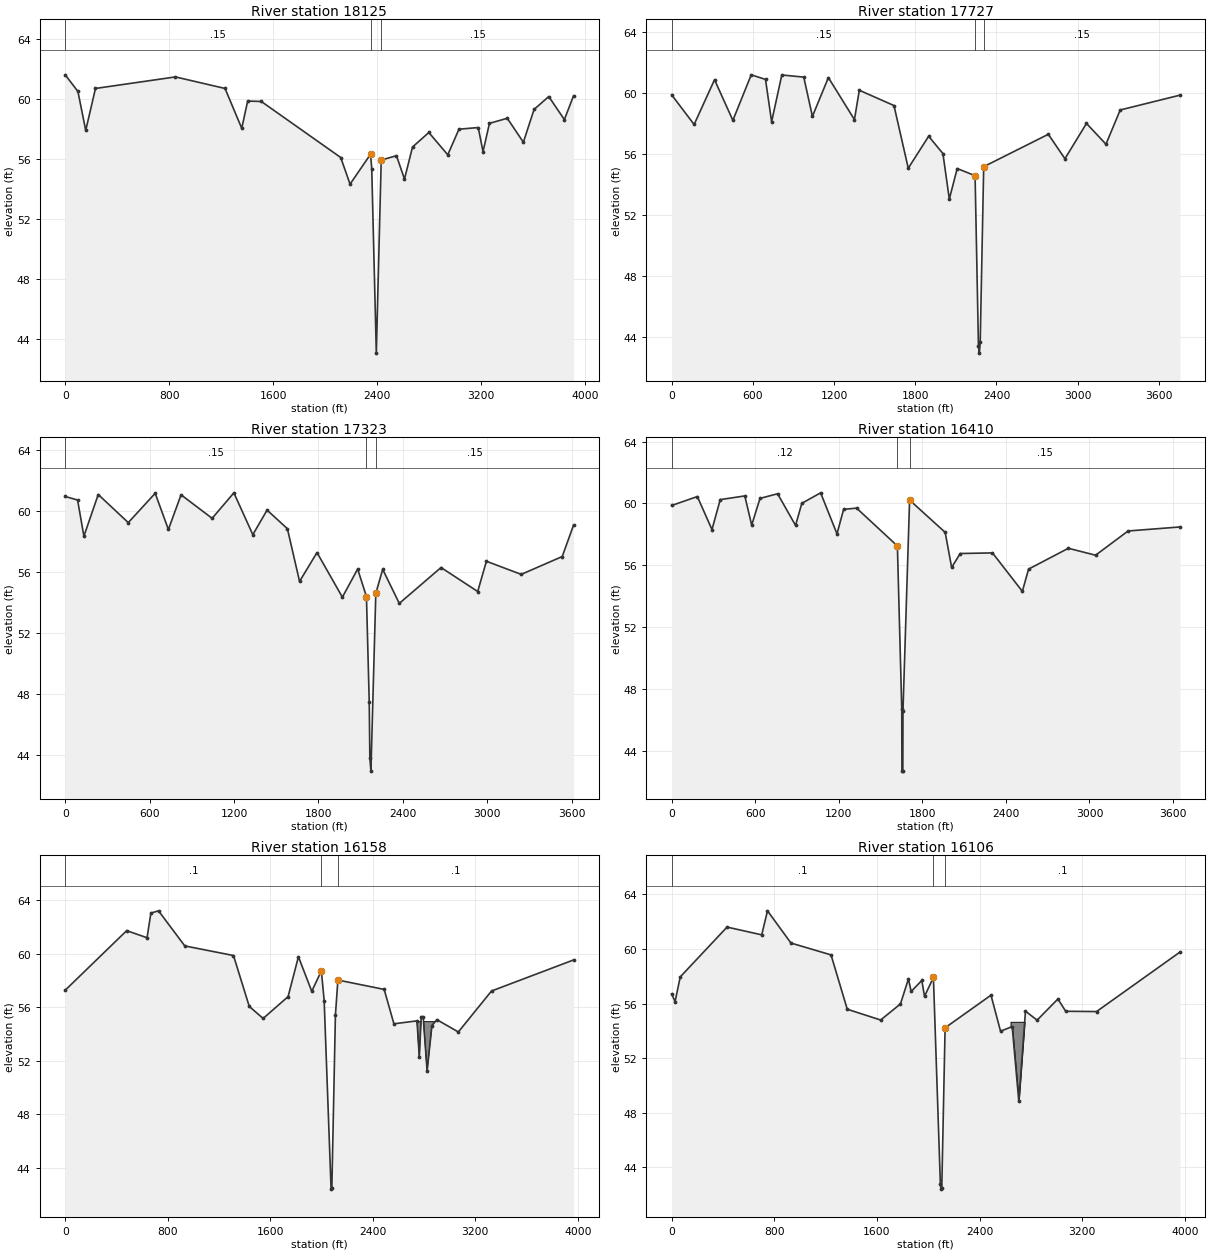
Type RM Length L Ch R = 1 ,18125   ,366.61,397.34,388.66
BEGIN DESCRIPTION:
18124.65--d/s exit Landsdowne bridge; channel copied from 18167
END DESCRIPTION:
XS GIS Cut Line= 5
     3084155.735    13803105.212     3084262.491    13800759.463
     3084282.914    13800664.917     3084550.848    13799613.973
     3084572.822    13799232.172
#Sta/Elev= 30
       0   61.62   97.81   60.51  157.88   57.91  232.95   60.71  848.59   61.48
 1229.84   60.71 1358.56   58.05 1404.16   59.87 1509.27   59.84 2120.27    56.1
 2192.08   54.32 2349.84   56.32 2359.02   55.35  2394.2   43.04 2431.98   55.93
 2549.34   56.22 2611.02   54.66 2672.69    56.8 2798.27   57.77 2944.06   56.28
 3030.17   57.99 3178.43    58.1 3215.43   56.49 3264.77   58.38 3401.99   58.72
 3525.82   57.12  3608.2   59.31 3721.25   60.17 3841.45   58.63  3911.9   60.22
#Mann= 3 , 0 , 0
       0     .15       0 2349.84     .04       0 2431.98     .15       0
#XS Ineff= 2 , 0
       0    2341            2435       0
Permanent Ineff=
       T       T
Bank Sta=2349.84,2431.98
XS Rating Curve= 0
Exp/Cntr=.3,.1

Type RM Length L Ch R = 1 ,17727   ,321.33,404.5,448.75
BEGIN DESCRIPTION:
 17727.31--surveyed channel
END DESCRIPTION:
XS GIS Cut Line= 5
     3084424.029     13803097.66     3084636.399    13800890.017
     3084658.485    13800792.883     3084809.576    13800090.904
     3084850.117    13799371.304
#Sta/Elev= 30
       0   59.86  165.92   57.92  316.61   60.85  452.24   58.19  587.86   61.17
  693.35   60.87  738.55    58.1   813.9   61.16  976.14   61.02 1039.94   58.45
 1158.06   60.99 1350.52   58.24 1386.53   60.16 1642.71   59.16 1748.19   55.06
 1898.89   57.15 2004.37   56.02 2051.61   53.04 2109.85   55.04 2242.06   54.57
 2266.92   43.44 2273.43   42.96 2279.98   43.71 2305.74   55.16 2783.26   57.28
 2906.01   55.68 3065.21   57.99 3209.18   56.63 3314.35   58.87 3756.24   59.84
#Mann= 3 , 0 , 0
       0     .15       0 2242.06     .04       0 2305.74     .15       0
#XS Ineff= 2 , 0
       0    2219            2310       0
Permanent Ineff=
       T       T
Bank Sta=2242.06,2305.74
XS Rating Curve= 0
Exp/Cntr=.3,.1

Type RM Length L Ch R = 1 ,17323   ,798.97,912.78,584.32
BEGIN DESCRIPTION:
 17322.81--surveyed channel
END DESCRIPTION:
XS GIS Cut Line= 6
     3084781.776     13803110.31     3084844.651    13801469.853
     3085012.365    13801020.905     3085045.382    13800927.223
     3085229.034    13800410.664     3085254.527    13799566.827
#Sta/Elev= 30
       0   60.93   87.87    60.7  132.91   58.33  234.72   61.06  448.14   59.22
  639.51   61.14  733.35   58.77  823.41   61.04  1044.3    59.5 1198.69   61.17
 1333.44   58.43 1434.64   60.04 1579.21   58.82 1665.52   55.37 1789.48   57.26
 1969.76   54.34 2078.44   56.18 2140.93   54.38 2160.68    47.5 2165.06   43.84
 2172.69   42.95  2207.5   54.59 2256.42   56.16 2374.36   53.93 2671.01   56.28
 2931.72   54.71 2993.42   56.69 3241.05   55.83 3532.39      57  3612.7   59.05
#Mann= 3 , 0 , 0
       0     .15       0 2140.93     .04       0  2207.5     .15       0
#XS Ineff= 2 , 0
       0    2109            2215       0
Permanent Ineff=
       T       T
Bank Sta=2140.93,2207.5
XS Rating Curve= 0
Exp/Cntr=.3,.1

Type RM Length L Ch R = 1 ,16410   ,331.87,252.36,241.34
BEGIN DESCRIPTION:
 16410.04--surveyed channel
END DESCRIPTION:
XS GIS Cut Line= 6
     3085426.404    13803281.845     3085451.122    13802033.615
     3085580.388    13801697.804     3085619.865    13801605.733
      3085442.58    13800880.466      3085503.05    13799686.982
#Sta/Elev= 30
       0   59.87  184.38   60.45   289.4   58.31  348.61   60.25  525.15   60.49
  574.46    58.6  634.47   60.33  760.53   60.63  889.52   58.58  934.53   60.01
 1069.55   60.69 1187.17   58.03 1234.59   59.62 1327.77    59.7 1620.84   57.25
  1652.2   46.68 1653.28   42.68 1659.91   42.67  1660.9   46.57 1708.37   60.22
 1964.03   58.13 2010.35   55.86 2072.12   56.76 2303.74    56.8 2518.15   54.31
 2562.69   55.75 2848.58    57.1 3043.83   56.65 3277.43   58.22 3650.12   58.48
#Mann= 3 , 0 , 0
       0     .12       0 1620.84     .04       0 1708.37     .15       0
#XS Ineff= 2 , 0
       0    1593            1715       0
Permanent Ineff=
       T       T
Bank Sta=1620.84,1708.37
XS Rating Curve= 0
Exp/Cntr=.3,.1

Type RM Length L Ch R = 1 ,16158   ,47.77,52.07,58.99
BEGIN DESCRIPTION:
16157.68--u/s approach Chimney Rock West bridge; channel copied from 15814; blocked obstruction in D139 channel
END DESCRIPTION:
XS GIS Cut Line= 6
     3086283.788    13803570.887     3086319.846    13802191.669
     3085853.052    13801742.939     3085854.088     13801643.54
     3085657.754    13801358.719      3085917.02    13799887.126
#Sta/Elev= 30
       0   57.27  479.72   61.72  638.61   61.19  668.62   63.03  728.31    63.2
  933.03   60.58 1313.23   59.86 1436.21   56.06 1544.43   55.16 1739.23   56.79
 1819.89   59.77 1923.92   57.19 1998.96   58.71 2020.85    56.5 2074.85   42.41
 2080.76   42.47 2108.58    55.4 2127.86   58.03    2489   57.33 2565.15   54.76
  2745.3   54.98 2763.15   52.28 2778.38   55.29 2793.62   55.29 2824.08   51.23
 2861.85   54.63 2900.23   55.07 3067.77   54.15  3326.7   57.21 3966.78   59.53
#Mann= 3 , 0 , 0
       0      .1       0 1998.96     .04       0 2127.86      .1       0
#XS Ineff= 2 , 0
       0    1937            2161       0
Permanent Ineff=
       T       T
#Block Obstruct= 1 ,-1
 2745.12 2887.81   54.92
Bank Sta=1998.96,2127.86
XS Rating Curve= 0
Exp/Cntr=.5,.3

Type RM Length L Ch R = 1 ,16106   ,42.2,49.1,61.38
BEGIN DESCRIPTION:
16105.60--u/s face Chimney Rock West bridge; channel copied from 15814; blocked obstruction in D139 channel
END DESCRIPTION:
XS GIS Cut Line= 6
     3086335.365    13803588.931     3086371.847    13802193.979
     3085905.053    13801745.249     3085906.089     13801645.85
     3085709.755    13801361.029     3085965.328    13799910.482
#Sta/Elev= 30
       0   56.71   26.44   56.15   66.84   57.96  431.58   61.61  701.67   61.04
  746.69    62.8  929.58   60.44 1241.86   59.57 1368.26   55.59 1628.44    54.8
 1782.92   55.98 1844.88   57.81 1866.14   56.89 1949.37    57.7 1970.18   56.53
 2039.68   57.92  2093.9   42.79 2098.85   42.41 2104.76   42.47 2130.68   54.23
 2488.27   56.62 2562.75   53.98 2653.39   54.32 2705.08   48.85 2756.99   55.45
 2847.64   54.79 3009.71   56.34 3070.63   55.44 3310.92   55.42 3961.16   59.78
#Mann= 3 , 0 , 0
       0      .1       0 2039.68     .04       0 2130.68      .1       0
#XS Ineff= 2 , 0
       0    1960            2199       0
Permanent Ineff=
       T       T
#Block Obstruct= 1 ,-1
 2640.49 2754.99   54.67
Bank Sta=2039.68,2130.68
XS Rating Curve= 0
Exp/Cntr=.5,.3

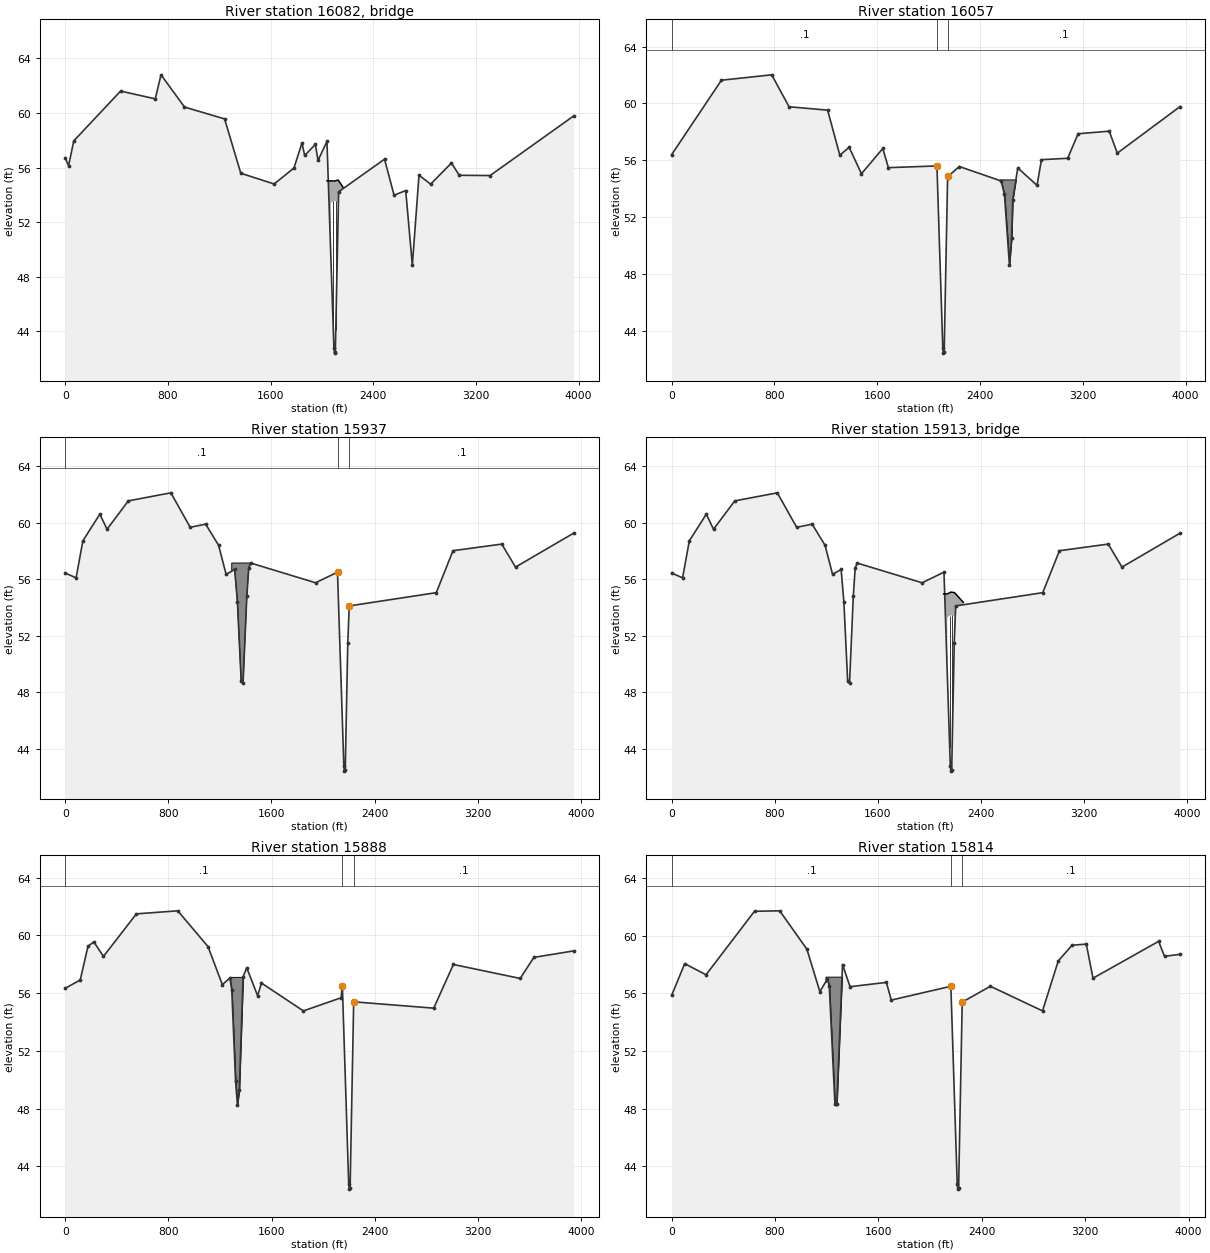
Type RM Length L Ch R = 3 ,16082   ,,,
BEGIN DESCRIPTION:
Chimney Rock West (U/S) Bridge
END DESCRIPTION:
Bridge Culvert--1,0,-1,-1, 0
Deck Dist Width WeirC Skew NumUp NumDn MinLoCord MaxHiCord MaxSubmerge Is_Ogee
5,38,2.6,0, 7, 7, , , .95, 0, 0,0,,
    2040 2070.28 2070.28 2098.83 2127.37 2127.37 2164.62
   55.03   55.03   55.03   55.02   55.09   55.09   54.57
     -.1     -.1   53.44   53.57   53.44     -.1     -.1
    2056 2086.28 2086.28 2114.83 2143.37 2143.37 2180.62
   55.03   55.03   55.03   55.02   55.09   55.09   54.57
     -.1     -.1   53.44   53.57   53.44     -.1     -.1
Pier Skew, UpSta & Num, DnSta & Num=  ,2089.31, 2 ,2105.31, 2 , 0 , 0 , 0 ,,
     .63     .63
       0   53.57
     .63     .63
       0   53.57
Pier Skew, UpSta & Num, DnSta & Num=  ,2108.34, 2 ,2124.34, 2 , 0 , 0 , 0 ,,
     .63     .63
       0   53.57
     .63     .63
       0   53.57
BR Coef=-1 , 1 , 1 ,1.05, 0 ,,,.8,-1,1.2,0,
WSPro=,,,, 1 ,,,, 0 ,,,, 0 ,,,,-1 ,-1 ,-1 , 0 , 0 , 0 , 0 , 0
BC Design=,, 0 ,, 0 ,,,,,,

Type RM Length L Ch R = 1 ,16057   ,104.67,119.67,164.93
BEGIN DESCRIPTION:
16056.51--d/s face Chimney Rock West bridge; channel copied from 15814; blocked obstruction in D139 channel
END DESCRIPTION:
XS GIS Cut Line= 6
     3086383.655    13803605.824     3086420.718    13802189.299
     3085953.924    13801740.569      3085954.96     13801641.17
     3085758.626    13801356.349     3086009.621    13799931.897
#Sta/Elev= 30
       0    56.4  387.17   61.64  778.59   62.02  913.59   59.77 1213.74   59.53
  1308.4   56.36 1381.51   56.91 1476.96   55.05 1643.26   56.83 1686.55   55.48
 2064.51    55.6  2109.9   42.79 2114.85   42.41 2120.76   42.47 2147.58   54.77
 2150.27   54.86 2238.73   55.56    2564   54.54 2589.89    53.6 2628.74   48.62
 2645.76   50.51 2654.64   53.21 2693.49   55.46 2843.76   54.23 2877.93   56.04
 3081.97   56.14 3163.62   57.87  3405.7   58.05 3468.24    56.5 3956.24   59.78
#Mann= 3 , 0 , 0
       0      .1       0 2064.51     .04       0 2150.27      .1       0
#XS Ineff= 2 , 0
       0    1983            2229       0
Permanent Ineff=
       T       T
#Block Obstruct= 1 ,-1
 2551.04 2680.75   54.65
Bank Sta=2064.51,2150.27
XS Rating Curve= 0
Exp/Cntr=.5,.3

Type RM Length L Ch R = 1 ,15937   ,44.83,49.1,59.18
BEGIN DESCRIPTION:
15936.84--u/s face Chimney Rock East bridge; channel & LOB copied from 15814; blocked obstruction in D139 channel
END DESCRIPTION:
XS GIS Cut Line= 6
     3086501.367    13803647.005     3086539.841    13802177.889
     3086073.047    13801729.159     3086074.083     13801629.76
     3085877.749    13801344.939     3086117.584    13799984.095
#Sta/Elev= 30
       0   56.44   84.53    56.1   137.1   58.72   268.7   60.61  324.62   59.54
  489.67   61.55  819.79   62.12  969.84   59.68 1089.88    59.9 1189.89   58.41
 1248.38   56.35 1314.96   56.69 1336.12   54.41 1365.36   48.82 1379.98   48.65
 1409.23   54.79 1423.85   56.77 1438.47   57.15 1942.85   55.75 2112.85    56.5
  2161.9   42.79 2166.85   42.41 2172.76   42.47 2192.45   51.46 2203.78   54.11
 2879.44   55.05 3008.93   58.02 3387.42   58.49 3494.04   56.86 3944.27   59.26
#Mann= 3 , 0 , 0
       0      .1       0 2112.85     .04       0 2203.78      .1       0
#XS Ineff= 2 , 0
       0    2049            2305       0
Permanent Ineff=
       T       T
#Block Obstruct= 1 ,-1
 1292.13 1438.48   57.15
Bank Sta=2112.85,2203.78
XS Rating Curve= 0
Exp/Cntr=.5,.3

Type RM Length L Ch R = 3 ,15913   ,,,
BEGIN DESCRIPTION:
Chimney Rock East (D/S) Bridge
END DESCRIPTION:
Bridge Culvert--1,0,-1,-1, 0
Deck Dist Width WeirC Skew NumUp NumDn MinLoCord MaxHiCord MaxSubmerge Is_Ogee
5,38,2.6,0, 7, 7, , , .95, 0, 0,0,,
    2110 2138.61 2138.61 2166.83 2195.04 2195.04 2263.36
   54.96   54.96   54.96   55.09   55.05   55.05   54.36
     -.1     -.1   53.32   53.45   53.41     -.1     -.1
    2145 2173.61 2173.61 2201.83 2230.04 2230.04 2298.36
   54.96   54.96   54.96   55.09   55.05   55.05   54.36
     -.1     -.1   53.32   53.45   53.41     -.1     -.1
Pier Skew, UpSta & Num, DnSta & Num=  ,2157.42, 2 ,2192.42, 2 , 0 , 0 , 0 ,,
     .63     .63
       0   53.57
     .63     .63
       0   53.57
Pier Skew, UpSta & Num, DnSta & Num=  ,2176.23, 2 ,2211.23, 2 , 0 , 0 , 0 ,,
     .63     .63
       0   53.57
     .63     .63
       0   53.57
BR Coef=-1 , 1 , 1 ,1.05, 0 ,,,.8,-1,1.2,0,
WSPro=,,,, 1 ,,,, 0 ,,,, 0 ,,,,-1 ,-1 ,-1 , 0 , 0 , 0 , 0 , 0
BC Design=,, 0 ,, 0 ,,,,,,

Type RM Length L Ch R = 1 ,15888   ,111.59,73.35,83.18
BEGIN DESCRIPTION:
15887.75--d/s face Chimney Rock East bridge; channel copied from 15814; blocked obstruction in D139 channel
END DESCRIPTION:
XS GIS Cut Line= 6
     3086549.657    13803663.898     3086588.712    13802173.209
     3086121.918    13801724.479     3086122.954     13801625.08
      3085926.62    13801340.259     3086161.876    13800005.509
#Sta/Elev= 30
       0   56.34  116.44   56.91  176.46   59.25  221.47   59.56   296.5   58.55
  551.59    61.5   872.2   61.71 1106.78   59.23 1217.76   56.59 1276.25   57.05
 1290.88   56.22 1320.12   49.93 1334.74   48.24 1349.36   49.31 1378.61   57.13
 1406.88   57.76  1491.2   55.82 1521.08    56.7 1845.75   54.77 2137.89   55.68
 2147.85    56.5  2196.9   42.79 2201.85   42.41 2207.76   42.47 2235.58    55.4
 2855.92   54.96 3008.24   57.99  3526.1   57.02 3631.72   58.48 3939.36   58.93
#Mann= 3 , 0 , 0
       0      .1       0 2147.85     .04       0 2235.58      .1       0
#XS Ineff= 2 , 0
       0    2072            2338       0
Permanent Ineff=
       T       T
#Block Obstruct= 1 ,-1
  1271.7 1383.77   57.13
Bank Sta=2147.85,2235.58
XS Rating Curve= 0
Exp/Cntr=.5,.3

Type RM Length L Ch R = 1 ,15814   ,269.45,147.57,310.3
BEGIN DESCRIPTION:
15814.39--d/s exit Chimney Rock East bridge; surveyed channel; blocked obstruction in D139 channel
END DESCRIPTION:
XS GIS Cut Line= 6
     3086621.014    13803678.321     3086661.738    13802165.516
     3086194.944    13801716.786      3086195.98    13801617.387
     3085999.646    13801332.566     3086229.137    13800024.569
#Sta/Elev= 30
       0   55.87  100.86   58.07  265.92    57.3  641.05   61.71  836.12   61.74
  1046.2   59.08 1146.86   56.13 1205.31      57 1219.92   56.51 1263.76    48.3
 1271.28    48.3 1278.37   48.33 1322.21   58.01 1380.65   56.47    1662   56.77
 1699.56   55.54 2160.85    56.5  2209.9   42.79 2214.85   42.41 2220.76   42.47
 2248.58    55.4  2466.6    56.5 2870.23   54.79 2992.06   58.26 3098.67   59.35
 3209.01   59.43 3260.83   57.06 3768.75   59.62 3814.44   58.58 3934.17   58.72
#Mann= 3 , 0 , 0
       0      .1       0 2160.85     .04       0 2248.58      .1       0
#XS Ineff= 2 , 0
       0    2095            2366       0
Permanent Ineff=
       T       T
#Block Obstruct= 1 ,-1
  1190.6 1326.19   57.17
Bank Sta=2160.85,2248.58
XS Rating Curve= 0
Exp/Cntr=.3,.1

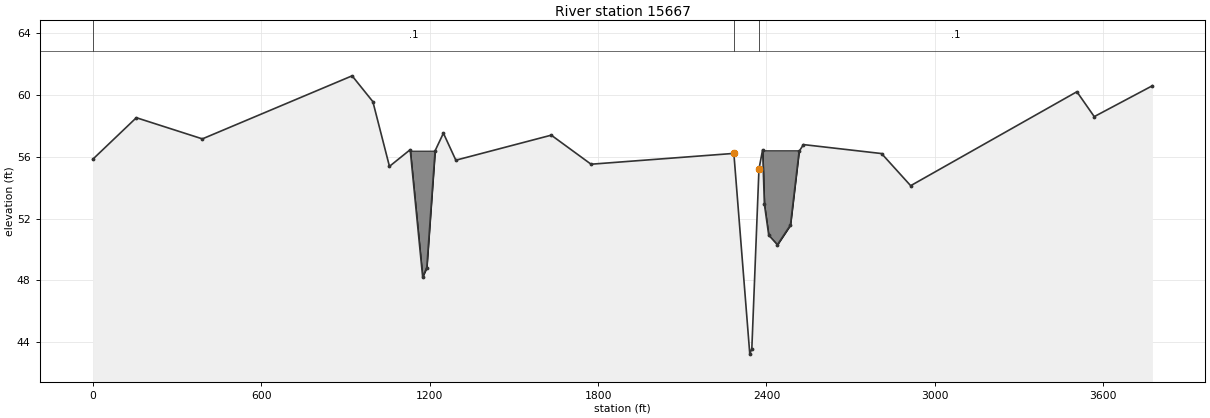
Type RM Length L Ch R = 1 ,15667   ,534.67,694.47,681.43
BEGIN DESCRIPTION:
15666.83--surveyed channel; blocked obstruction in D139 channel & anamolous hole in apt. parking lot
END DESCRIPTION:
XS GIS Cut Line= 5
     3086775.326    13803742.847     3086801.067     13802011.71
     3086340.827    13801706.049     3086344.064    13801603.578
     3086680.771    13800256.382
#Sta/Elev= 30
       0   55.84  155.23   58.53  390.39   57.16  923.89   61.24   997.8   59.57
 1056.92   55.38 1130.83   56.46 1175.18   48.23 1189.96   48.83 1219.52   56.39
 1249.09   57.53 1293.43   55.78 1633.42    57.4 1775.09   55.52 2283.82   56.22
 2340.61   43.23 2347.87   43.59 2373.28   55.21 2386.35   56.46 2392.61   52.93
 2408.07   50.93 2438.99   50.31 2485.38   51.58  2516.3   56.35 2531.76   56.79
 2810.07   56.21 2913.72   54.13 3505.83   60.21 3567.68    58.6 3774.98    60.6
#Mann= 3 , 0 , 0
       0      .1       0 2283.82     .04       0 2373.28      .1       0
#XS Ineff= 2 , 0
       0    2205            2437       0
Permanent Ineff=
       T       T
#Block Obstruct= 2 ,-1
  1130.8 1221.02    56.4 2386.35 2523.65   56.42
Bank Sta=2283.82,2373.28
XS Rating Curve= 0
Exp/Cntr=.3,.1