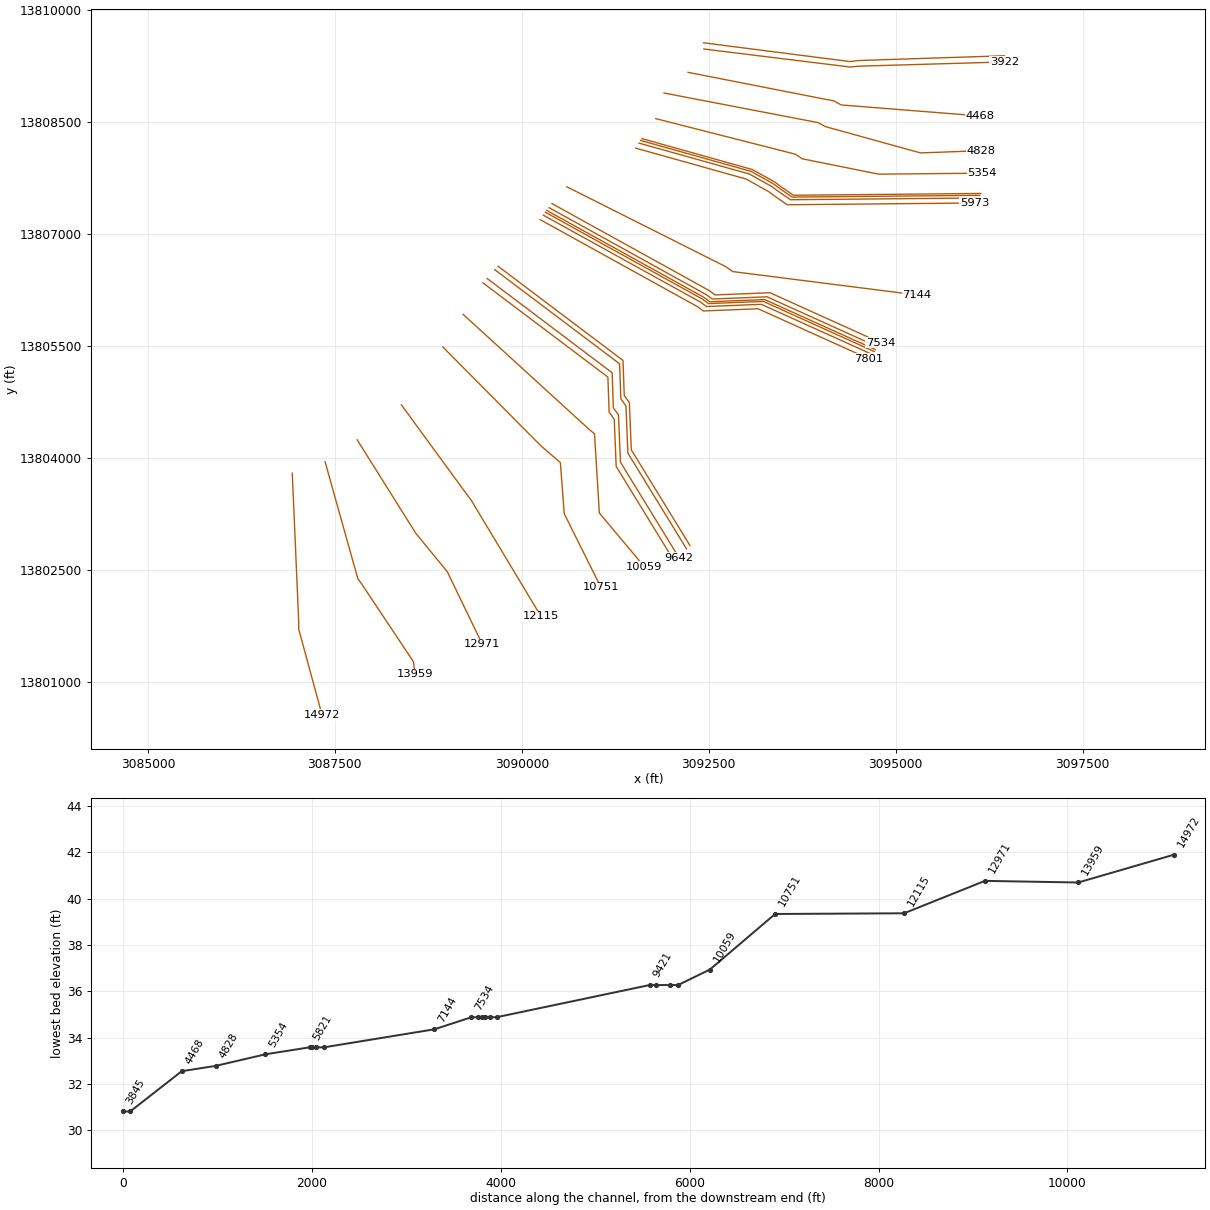
HEC-RAS study D112-00-00.prj: D112-00-00

--- D112-00-00.g05 (geometry) --- (continued)

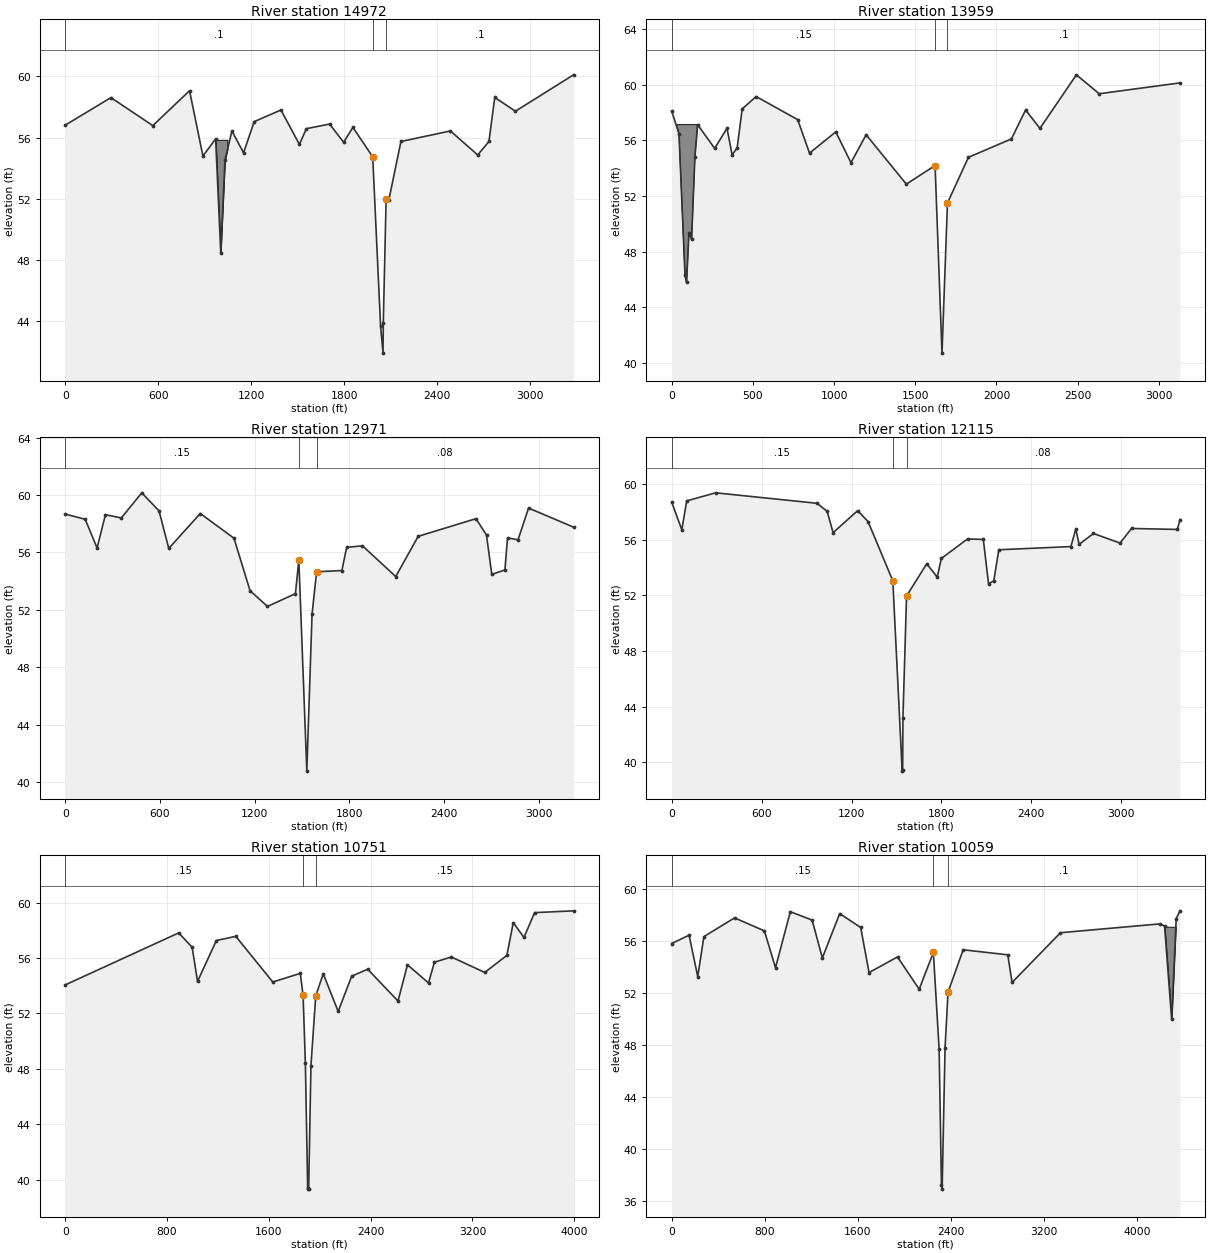
Type RM Length L Ch R = 1 ,14972   ,944.6,1012.84,1077.73
BEGIN DESCRIPTION:
14972.36--surveyed channel; blocked obstruction in D139 channel
END DESCRIPTION:
XS GIS Cut Line= 4
     3086930.953    13803797.292     3087016.902     13801814.85
     3087016.902     13801711.34     3087329.387    13800560.656
#Sta/Elev= 30
       0   56.81  295.07   58.61  565.32   56.78  802.34   59.06  888.68   54.79
   970.7   55.91  1003.8   48.46 1030.76   54.51 1075.75   56.43 1150.87      55
 1219.65   57.04 1392.34    57.8 1511.21   55.55 1556.25   56.58 1706.39   56.88
 1796.48   55.69 1856.53   56.66  1984.3   54.74 2035.12   43.65 2050.94    41.9
 2052.61   43.89 2070.79   51.95 2087.81   51.89 2166.41   55.74 2485.56   56.43
 2661.87   54.86 2734.25   55.74 2771.89   58.62 2905.22   57.72 3280.17    60.1
#Mann= 3 , 0 , 0
       0      .1       0  1984.3     .04       0 2070.79      .1       0
#XS Ineff= 2 , 0
       0    1977            2080       0
Permanent Ineff=
       T       T
#Block Obstruct= 1 ,-1
  970.69 1046.95   55.85
Bank Sta=1984.3,2070.79
XS Rating Curve= 0
Exp/Cntr=.3,.1

Type RM Length L Ch R = 1 ,13959   ,975.13,987.97,1031.83
BEGIN DESCRIPTION:
13959.52--surveyed channel; blocked obstruction in D139 channel
END DESCRIPTION:
XS GIS Cut Line= 5
     3087369.453    13803950.697     3087806.707    13802388.728
     3087858.404    13802315.523     3088551.812    13801273.391
      3088572.31    13801107.886
#Sta/Elev= 30
       0    58.1   44.86   56.49   82.14    46.3   91.59   45.78  106.48   49.36
  122.74   48.89  142.99   54.78  159.69   57.13  264.69   55.42  340.81   56.87
  371.97   54.96  403.12   55.45  434.27   58.26  520.26   59.15  775.82   57.49
  848.84   55.08 1010.61   56.61 1104.07   54.39 1197.53    56.4 1445.17   52.85
 1622.02   54.19 1664.59    40.7 1698.17   51.49 1827.34   54.78 2091.82    56.1
 2179.36   58.18 2267.79   56.86  2492.1   60.71 2632.74   59.35 3130.15   60.13
#Mann= 3 , 0 , 0
       0     .15       0 1622.02     .04       0 1698.17      .1       0
#XS Ineff= 2 , 0
       0    1615            1940       0
Permanent Ineff=
       T       T
#Block Obstruct= 1 ,-1
   31.15  159.76   57.13
Bank Sta=1622.02,1698.17
XS Rating Curve= 0
Exp/Cntr=.3,.1

Type RM Length L Ch R = 1 ,12971   ,857.32,856.21,824.73
BEGIN DESCRIPTION:
 12971.56--surveyed channel
END DESCRIPTION:
XS GIS Cut Line= 5
     3087798.992    13804243.565     3088585.166    13802989.215
     3088651.587    13802909.124      3089004.53    13802477.791
     3089473.372    13801505.802
#Sta/Elev= 30
       0   58.67  126.65   58.31  201.89   56.31     255   58.63  355.18    58.4
  485.13   60.15  594.58   58.89  656.24   56.28  855.76   58.71 1069.32   56.99
 1171.34   53.33 1281.75   52.24 1458.78   53.13 1480.36   55.47 1530.87   40.77
 1564.08    51.7 1592.97   54.65 1753.21   54.74 1783.24   56.35 1883.69   56.46
 2094.31   54.32 2236.43   57.12 2602.82   58.35 2669.43   57.21 2702.74   54.47
 2786.01   54.78 2802.66   57.01 2869.28   56.88 2935.89   59.09 3220.89   57.76
#Mann= 3 , 0 , 0
       0     .15       0 1480.36     .04       0 1592.97     .08       0
#XS Ineff= 2 , 0
       0    1475            2236       0
Permanent Ineff=
       T       T
Bank Sta=1480.36,1592.97
XS Rating Curve= 0
Exp/Cntr=.3,.1

Type RM Length L Ch R = 1 ,12115   ,1210.4,1364.61,1321.84
BEGIN DESCRIPTION:
 12115.34--surveyed channel
END DESCRIPTION:
XS GIS Cut Line= 4
      3088390.74    13804710.523     3089260.845    13803519.019
     3089326.612    13803430.715     3090256.502    13801882.694
#Sta/Elev= 30
       0    58.7   67.83    56.7  100.04   58.78  293.26   59.36  969.55   58.61
 1037.33   58.03 1076.89    56.5  1240.8   58.08  1310.1    57.3 1475.39   53.04
 1537.86   39.37 1541.03   39.43 1542.86    43.2 1567.03   51.95 1701.44   54.26
  1771.7   53.31 1799.22   54.65  1974.2   56.05 2079.19   56.01 2114.19   52.82
 2149.18   53.05 2182.43   55.27 2663.43    55.5 2696.22   56.76 2718.08   55.66
 2814.12   56.44 2991.37   55.75  3067.9    56.8 3373.85   56.73 3391.33   57.44
#Mann= 3 , 0 , 0
       0     .15       0 1475.39     .04       0 1567.03     .08       0
#XS Ineff= 2 , 0
       0    1470            2190       0
Permanent Ineff=
       T       T
Bank Sta=1475.39,1567.03
XS Rating Curve= 0
Exp/Cntr=.3,.1

Type RM Length L Ch R = 1 ,10751   ,682.66,691.3,542.7
BEGIN DESCRIPTION:
 10750.73--surveyed channel
END DESCRIPTION:
XS GIS Cut Line= 6
     3088943.941    13805486.082     3090250.892    13804167.179
      3090335.95    13804094.441     3090516.437    13803938.447
     3090567.688    13803255.099     3091058.938    13802268.877
#Sta/Elev= 30
       0   54.06  891.97   57.81  997.56   56.77 1039.79   54.31 1187.61   57.26
 1340.51   57.56 1631.08   54.27 1847.08   54.89 1869.22   53.32 1887.24    48.4
 1905.14   39.41 1909.86   39.34 1913.08   39.35    1931   48.25  1968.7   53.28
 2027.89   54.86 2144.87   52.15 2251.11   54.69 2377.04   55.19 2614.92    52.9
 2689.55   55.51 2855.01    54.2 2901.01    55.7 3035.07   56.07 3297.01   54.96
 3470.78   56.19 3520.73   58.55 3604.84   57.48 3688.31   59.27 3994.32    59.4
#Mann= 3 , 0 , 0
       0     .15       0 1869.22    .017       0  1968.7     .15       0
#XS Ineff= 2 , 0
       0    1860            2693       0
Permanent Ineff=
       T       T
Bank Sta=1869.22,1968.7
XS Rating Curve= 0
Exp/Cntr=.3,.1

Type RM Length L Ch R = 1 ,10059   ,383.46,336.8,325.66
BEGIN DESCRIPTION:
10059.43--surveyed channel; blocked obstruction in ditch
END DESCRIPTION:
XS GIS Cut Line= 5
     3089215.644    13805922.255     3090893.767     13804389.57
     3090972.857    13804322.428     3091037.489    13803263.641
     3091637.672      13802547.4
#Sta/Elev= 30
       0    55.8  149.78   56.44  224.11   53.26  277.19   56.33  540.87   57.77
  797.45   56.77  893.01   53.94 1020.42   58.24 1208.14    57.6 1295.89   54.69
 1445.12    58.1 1625.61   57.03 1697.48   53.57 1942.14   54.77 2128.79   52.29
 2250.68   55.12 2300.12   47.68 2320.05   37.25 2326.11   36.94 2351.12    47.8
 2376.46   52.05 2506.63   55.32 2890.66   54.93 2927.41   52.81 3343.88   56.63
 4201.94   57.31 4239.07   57.13 4299.79   49.99 4338.93   57.71 4371.68   58.31
#Mann= 3 , 0 , 0
       0     .15       0 2250.68    .017       0 2376.46      .1       0
#XS Ineff= 2 , 0
       0    2240            2731       0
Permanent Ineff=
       T       T
#Block Obstruct= 1 ,-1
 4237.08 4341.36   57.09
Bank Sta=2250.68,2376.46
XS Rating Curve= 0
Exp/Cntr=.3,.1

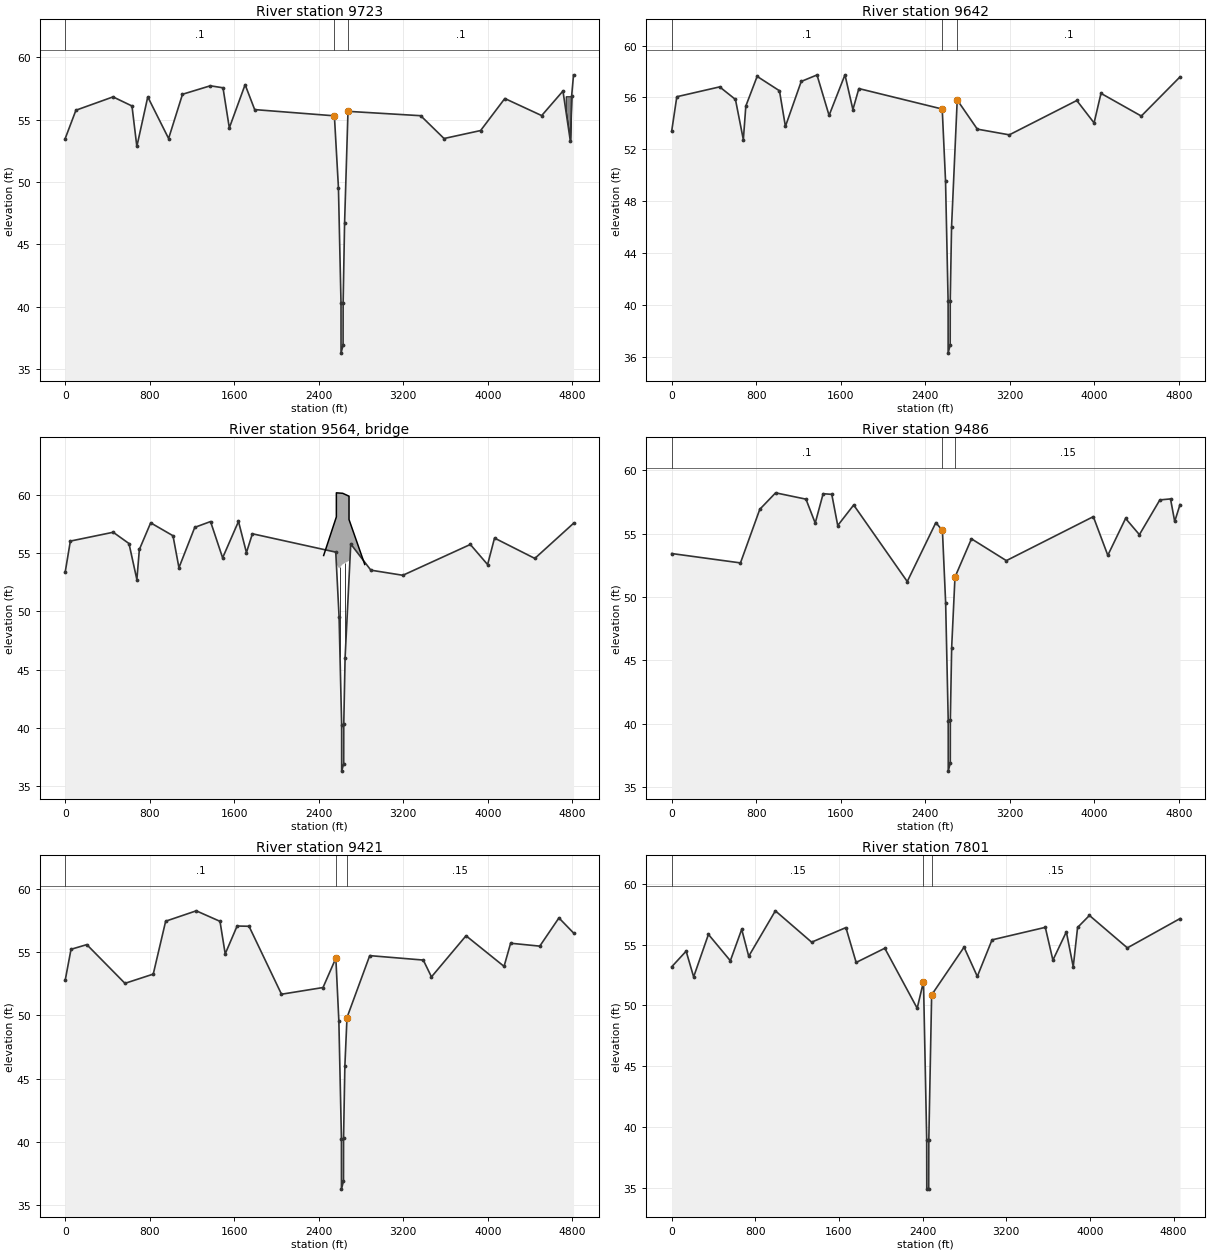
Type RM Length L Ch R = 1 ,9723    ,79.26,80.67,80
BEGIN DESCRIPTION:
9722.636--u/s approach Post Oak bridges;  channel copied from 9421; blocked obstruction in ditch
END DESCRIPTION:
XS GIS Cut Line= 6
     3089481.105    13806343.204     3091151.617     13805082.91
     3091168.438     13804613.73     3091236.851    13804517.996
     3091262.661     13803887.05     3092046.741    13802607.154
#Sta/Elev= 30
       0   53.49  101.46   55.76  452.71   56.83  632.12    56.1  678.19   52.85
  781.56   56.83  978.83   53.49 1110.36   57.04 1373.42   57.72 1493.76   57.56
 1553.64   54.34 1703.08   57.81 1793.64   55.81  2548.3   55.31 2586.61   49.55
 2611.01   40.26 2611.29   36.27 2630.48   36.91 2631.05    40.3 2644.72   46.69
 2676.98   55.67 3365.31   55.32 3586.28   53.49 3932.55   54.13 4161.62    56.7
 4510.69   55.33  4712.1    57.3 4782.46   53.26  4794.3    56.9 4812.19    58.6
#Mann= 3 , 0 , 0
       0      .1       0  2548.3    .017       0 2676.98      .1       0
#XS Ineff= 2 , 0
       0    2505            2698       0
Permanent Ineff=
       T       T
#Block Obstruct= 1 ,-1
 4737.59 4801.52   56.88
Bank Sta=2548.3,2676.98
XS Rating Curve= 0
Exp/Cntr=.5,.3

Type RM Length L Ch R = 1 ,9642    ,141.4,155.76,141.37
BEGIN DESCRIPTION:
9641.965--u/s face Post Oak bridges;  channel copied from 9421
END DESCRIPTION:
XS GIS Cut Line= 6
     3089537.905    13806401.124     3091208.417     13805140.83
     3091225.238     13804671.65     3091293.651    13804575.916
     3091319.461     13803944.97     3092103.541    13802665.074
#Sta/Elev= 30
       0   53.39   48.71   56.05  454.33   56.81  603.76   55.84  678.48   52.74
  702.02   55.33  809.12   57.62 1020.42   56.51 1076.79   53.76 1226.41   57.23
 1375.85   57.73 1490.17   54.61 1640.49   57.74 1715.65   55.06 1772.02   56.68
 2561.23    55.1 2592.61   49.55 2617.01   40.26 2617.29   36.27 2636.48   36.91
 2637.05    40.3 2649.54   46.01 2703.18    55.8 2893.45   53.55 3196.32   53.11
 3835.19   55.76 3998.81   54.03 4064.26   56.31 4445.79   54.56 4812.19   57.58
#Mann= 3 , 0 , 0
       0      .1       0 2561.23    .017       0 2703.18      .1       0
#XS Ineff= 2 , 0
       0    2554            2710       0
Permanent Ineff=
       T       T
Bank Sta=2561.23,2703.18
XS Rating Curve= 0
Exp/Cntr=.5,.3

Type RM Length L Ch R = 3 ,9564    ,,,
BEGIN DESCRIPTION:
Post Oak (modeled as one bridge) Bridge
END DESCRIPTION:
Bridge Culvert--1,0,-1,-1, 0
Deck Dist Width WeirC Skew NumUp NumDn MinLoCord MaxHiCord MaxSubmerge Is_Ogee
7,141,2.6,0, 7, 7, , , .95, 0, 0,0,,
 2446.56 2566.95 2566.95 2626.89 2686.85 2686.85 2835.76
   54.81   58.13    60.2   60.16   59.91    57.9   54.04
     -.1     -.1   53.43   54.06   54.35     -.1     -.1
 2447.56 2567.95 2567.95 2627.89 2687.85 2687.85 2836.76
   54.81   58.13    60.2   60.16   59.91    57.9   54.04
     -.1     -.1   53.43   54.06   54.35     -.1     -.1
Pier Skew, UpSta & Num, DnSta & Num=  ,2601.73, 2 ,2602.73, 2 , 0 , 0 , 0 ,,
    2.53    2.53
       0    56.9
    2.53    2.53
       0    56.9
Pier Skew, UpSta & Num, DnSta & Num=  ,2652.06, 2 ,2653.06, 2 , 0 , 0 , 0 ,,
    2.53    2.53
       0    56.7
    2.53    2.53
       0    56.7
BR Coef=-1 , 1 , 1 ,1.05, 0 ,,,.8,-1,1.2,0,
WSPro=,,,, 1 ,,,, 0 ,,,, 0 ,,,,-1 ,-1 ,-1 , 0 , 0 , 0 , 0 , 0
BC Design=,, 0 ,, 0 ,,,,,,

Type RM Length L Ch R = 1 ,9486    ,66.1,65.44,64.36
BEGIN DESCRIPTION:
9486.202--d/s face Post Oak bridges;  channel copied from 9421
END DESCRIPTION:
XS GIS Cut Line= 6
     3089637.561    13806520.834     3091308.073     13805260.54
     3091324.894     13804791.36     3091393.307    13804695.626
     3091419.117     13804064.68     3092203.197    13802784.784
#Sta/Elev= 30
       0   53.44  651.31    52.7  834.15   56.93  984.09   58.23 1271.38   57.73
 1358.94   55.84 1433.91   58.16 1515.65   58.11 1572.02   55.65 1723.08   57.27
 2230.22   51.23  2500.9   55.88 2563.13   55.26 2593.61   49.55 2618.01   40.26
 2618.29   36.27 2637.48   36.91 2638.05    40.3 2650.54   46.01 2681.97   51.58
    2838    54.6 3168.27   52.88 3991.58   56.35 4128.82    53.3 4297.01   56.21
 4427.86   54.93 4621.36   57.67 4722.44   57.75 4762.09   55.97 4812.18    57.3
#Mann= 3 , 0 , 0
       0      .1       0 2563.13    .017       0 2681.97     .15       0
#XS Ineff= 2 , 0
       0    2560            2716       0
Permanent Ineff=
       T       T
Bank Sta=2563.13,2681.97
XS Rating Curve= 0
Exp/Cntr=.5,.3

Type RM Length L Ch R = 1 ,9421    ,1549.38,1620.04,1803.98
BEGIN DESCRIPTION:
9420.765--d/s exit Post Oak bridges; surveyed channel
END DESCRIPTION:
XS GIS Cut Line= 6
      3089683.33    13806565.664     3091353.842     13805305.37
     3091370.663     13804836.19     3091439.076    13804740.456
     3091464.886     13804109.51     3092248.967    13802829.614
#Sta/Elev= 30
       0   52.78   55.07   55.22   204.5   55.59  565.73   52.53  833.48   53.26
  950.99   57.44 1240.46   58.26 1465.37   57.43 1514.69   54.86 1627.43   57.06
 1740.17   57.04 2047.55   51.67 2440.69    52.2 2562.08   54.52 2590.61   49.55
 2615.01   40.26 2615.29   36.27 2634.48   36.91 2635.05    40.3 2647.54   46.01
 2667.69   49.83 2882.87   54.72  3389.8   54.37  3467.3   53.04 3794.39   56.29
 4154.52   53.87 4216.58    55.7 4492.68   55.47 4673.94    57.7 4812.19   56.51
#Mann= 3 , 0 , 0
       0      .1       0 2562.08    .017       0 2667.69     .15       0
#XS Ineff= 2 , 0
       0    2555            2705       0
Permanent Ineff=
       T       T
Bank Sta=2562.08,2667.69
XS Rating Curve= 0
Exp/Cntr=.3,.1

Type RM Length L Ch R = 1 ,7801    ,73.34,73,75.01
BEGIN DESCRIPTION:
7800.723--u/s approach Willowbend South bridge; channel copied from 7534
END DESCRIPTION:
XS GIS Cut Line= 5
     3090246.497      13807189.2     3092347.475     13806026.62
     3092427.917    13805967.321     3093161.357      13805996.7
     3094642.698    13805326.573
#Sta/Elev= 30
       0   53.18  138.29   54.47  210.05   52.35  351.47   55.85  561.16   53.68
  669.74   56.27  736.73   54.05  991.58   57.79 1338.33   55.21 1666.15   56.41
 1764.13   53.54 2037.93   54.71 2347.74   49.77 2408.11   51.96 2438.81   38.96
 2439.51   34.93 2457.95   34.88 2458.96   38.92 2486.02   50.87 2795.94    54.8
 2922.74   52.39 3063.49    55.4 3572.88   56.43 3645.67   53.73 3774.21   56.06
 3840.07   53.18 3881.54   56.42 3994.89   57.41 4357.63   54.74 4861.02   57.15
#Mann= 3 , 0 , 0
       0     .15       0 2408.11    .017       0 2486.02     .15       0
#XS Ineff= 2 , 0
       0    2400            2496       0
Permanent Ineff=
       T       T
Bank Sta=2408.11,2486.02
XS Rating Curve= 0
Exp/Cntr=.5,.3

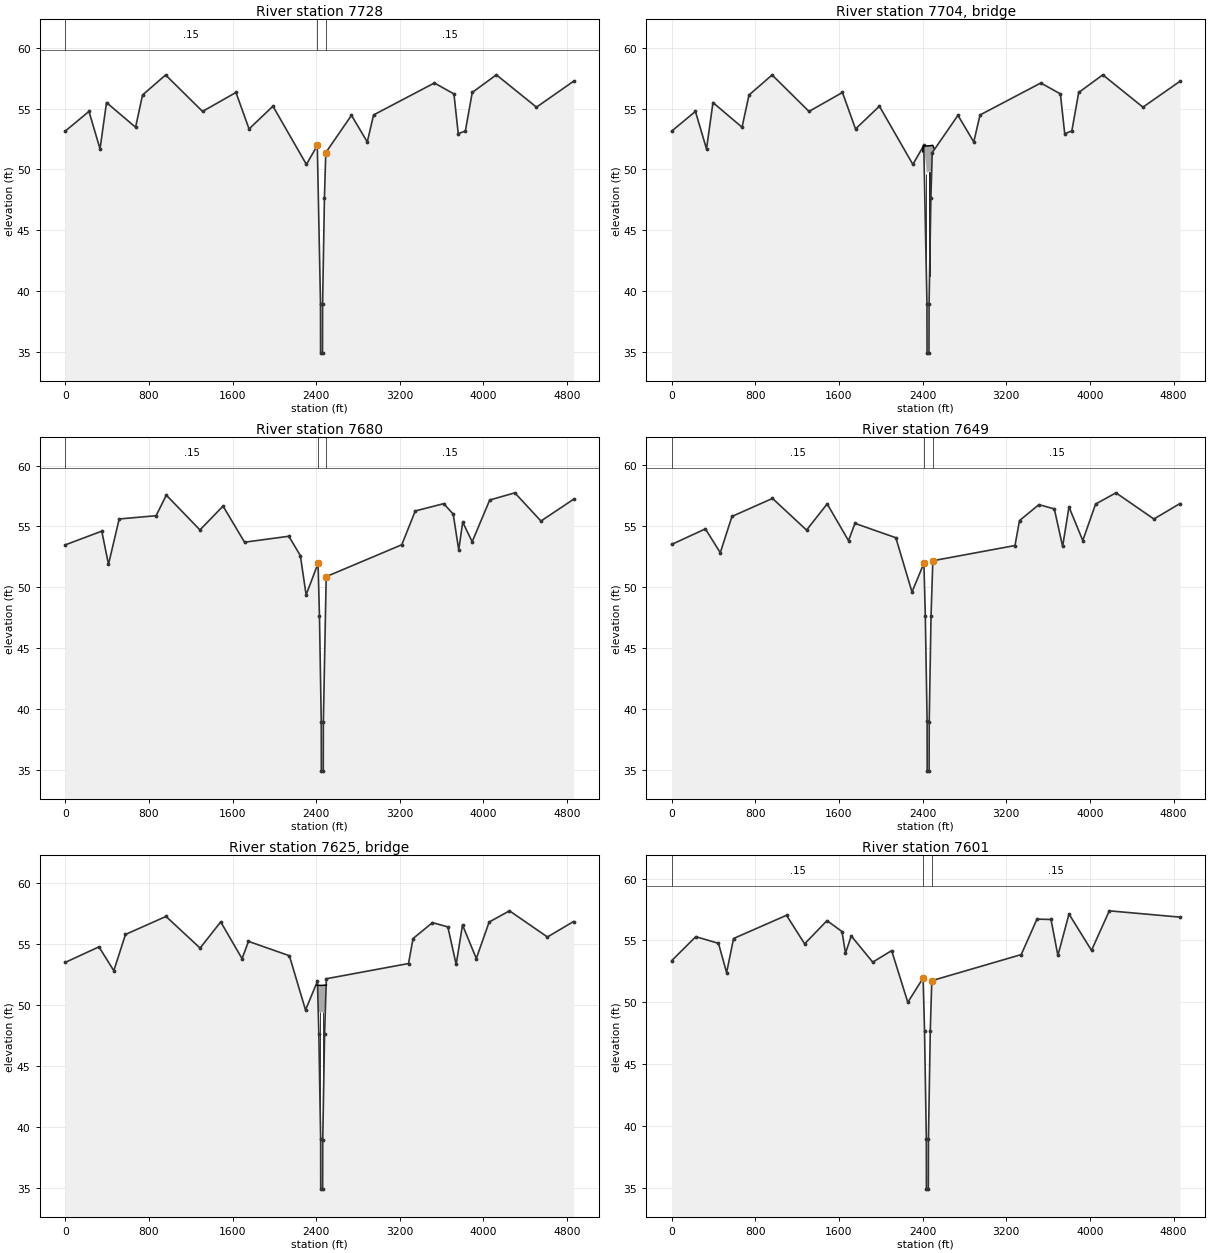
Type RM Length L Ch R = 1 ,7728    ,48.23,48,49.32
BEGIN DESCRIPTION:
7727.719--u/s face Willowbend South bridge; channel copied from 7534
END DESCRIPTION:
XS GIS Cut Line= 5
     3090288.742     13807248.74      3092389.72     13806086.16
     3092470.162    13806026.861     3093203.602     13806056.24
     3094684.943    13805386.113
#Sta/Elev= 30
       0   53.14  227.16   54.76  333.03   51.68  394.99   55.49  672.89   53.46
  739.44   56.11  960.16   57.76 1313.33   54.76 1632.91   56.32 1758.15   53.32
 1986.54   55.19  2306.6    50.4 2410.61   51.96 2441.31   38.96 2442.01   34.93
 2460.45   34.88 2461.46   38.92 2478.94   47.66 2491.76   51.37 2737.47   54.44
 2888.77   52.25 2948.82   54.47 3530.29    57.1 3717.34    56.2 3758.58   52.93
 3826.52   53.15 3892.48   56.32 4122.97   57.77 4506.72   55.11 4861.02   57.24
#Mann= 3 , 0 , 0
       0     .15       0 2410.61    .017       0 2491.76     .15       0
#XS Ineff= 2 , 0
       0    2400            2500       0
Permanent Ineff=
       T       T
Bank Sta=2410.61,2491.76
XS Rating Curve= 0
Exp/Cntr=.5,.3

Type RM Length L Ch R = 3 ,7704    ,,,
BEGIN DESCRIPTION:
Willowbend South (U/S) Bridge
END DESCRIPTION:
Bridge Culvert--1,0,-1,-1, 0
Deck Dist Width WeirC Skew NumUp NumDn MinLoCord MaxHiCord MaxSubmerge Is_Ogee
5,38,2.6,0, 7, 7, , , .95, 0, 0,0,,
  2400.4 2406.16 2406.16 2451.23 2496.02 2496.02 2507.48
   51.44   51.94   51.94   51.92   51.97   51.97   51.75
     -.1     -.1   49.21   49.79   49.84     -.1     -.1
  2407.4 2413.43 2413.43  2458.5 2503.29 2503.29 2514.75
   51.44   51.94   51.94   51.92   51.97   51.97   51.75
     -.1     -.1   49.21   49.79   49.84     -.1     -.1
Pier Skew, UpSta & Num, DnSta & Num=  ,2436.11, 2 ,2443.38, 2 , 0 , 0 , 0 ,,
     1.4     1.4
       0   49.83
     1.4     1.4
       0   49.83
Pier Skew, UpSta & Num, DnSta & Num=  ,2466.07, 2 ,2473.34, 2 , 0 , 0 , 0 ,,
     1.4     1.4
       0   49.93
     1.4     1.4
       0   49.93
BR Coef=-1 , 1 , 1 ,1.05, 0 ,,,.8,-1,1.2,0,
WSPro=,,,, 1 ,,,, 0 ,,,, 0 ,,,,-1 ,-1 ,-1 , 0 , 0 , 0 , 0 , 0
BC Design=,, 0 ,, 0 ,,,,,,

Type RM Length L Ch R = 1 ,7680    ,30.35,30.21,31.04
BEGIN DESCRIPTION:
7679.716--d/s face Willowbend South bridge; channel copied from 7534
END DESCRIPTION:
XS GIS Cut Line= 5
     3090316.519     13807287.89     3092417.497     13806125.31
     3092497.939    13806066.011     3093231.379     13806095.39
      3094712.72    13805425.263
#Sta/Elev= 30
       0   53.48   349.7   54.61  413.88   51.88  516.04   55.61   869.2   55.88
  966.86   57.57 1288.58   54.71 1509.31   56.67 1715.08    53.7 2138.38   54.19
 2248.75    52.6 2303.72   49.37 2417.88   51.96 2431.36   47.64 2448.58   38.96
 2449.28   34.93 2467.72   34.88 2468.73   38.92 2495.79   50.87 3218.48   53.49
 3347.76   56.27 3619.81   56.87  3710.5   56.01 3763.21   53.07 3801.18   55.35
 3891.86   53.74 4059.56   57.17 4299.94   57.76 4549.33   55.44 4861.02   57.23
#Mann= 3 , 0 , 0
       0     .15       0 2417.88    .017       0 2495.79     .15       0
#XS Ineff= 2 , 0
       0    2407            2505       0
Permanent Ineff=
       T       T
Bank Sta=2417.88,2495.79
XS Rating Curve= 0
Exp/Cntr=.5,.3

Type RM Length L Ch R = 1 ,7649    ,47.71,48.03,45.35
BEGIN DESCRIPTION:
7649.505--u/s face Willowbend North bridge; channel copied from 7534
END DESCRIPTION:
XS GIS Cut Line= 5
        3090334.     13807312.53     3092434.978     13806149.95
      3092515.42    13806090.651      3093248.86     13806120.03
     3094730.201    13805449.903
#Sta/Elev= 30
       0   53.51  322.65   54.79  464.78   52.83  576.49   55.81  964.03   57.29
 1289.75   54.69 1487.15   56.84 1691.16   53.82 1752.62   55.24 2143.65   54.06
 2298.16    49.6 2411.96   51.96 2425.44   47.64 2442.66   38.96 2443.36   34.93
  2461.8   34.88 2462.81   38.92 2480.29   47.66  2497.5   52.17 3283.05   53.42
 3326.21   55.47 3511.87   56.78 3659.23   56.43 3738.58   53.34 3799.32   56.59
 3931.28   53.83 4054.07   56.83 4248.67   57.75 4611.41    55.6 4861.02   56.87
#Mann= 3 , 0 , 0
       0     .15       0 2411.96    .017       0  2497.5     .15       0
#XS Ineff= 2 , 0
       0    2408            2508       0
Permanent Ineff=
       T       T
Bank Sta=2411.96,2497.5
XS Rating Curve= 0
Exp/Cntr=.5,.3

Type RM Length L Ch R = 3 ,7625    ,,,
BEGIN DESCRIPTION:
Willowbend North (D/S) Bridge
END DESCRIPTION:
Bridge Culvert--1,0,-1,-1, 0
Deck Dist Width WeirC Skew NumUp NumDn MinLoCord MaxHiCord MaxSubmerge Is_Ogee
5,38,2.6,0, 5, 5, , , .95, 0, 0,0,,
 2407.56 2407.56 2452.58  2497.6  2497.6
   51.63   51.63   51.62   51.65   51.65
     -.1   49.42   49.41   49.44     -.1
  2400.2  2400.2 2445.22 2490.24 2490.24
   51.63   51.63   51.62   51.65   51.65
     -.1   49.42   49.41   49.44     -.1
Pier Skew, UpSta & Num, DnSta & Num=  ,2437.57, 2 ,2430.21, 2 , 0 , 0 , 0 ,,
     1.4     1.4
       0   49.83
     1.4     1.4
       0   49.83
Pier Skew, UpSta & Num, DnSta & Num=  ,2467.59, 2 ,2460.23, 2 , 0 , 0 , 0 ,,
     1.4     1.4
       0   49.63
     1.4     1.4
       0   49.63
BR Coef=-1 , 1 , 1 ,1.05, 0 ,,,.8,-1,1.2,0,
WSPro=,,,, 1 ,,,, 0 ,,,, 0 ,,,,-1 ,-1 ,-1 , 0 , 0 , 0 , 0 , 0
BC Design=,, 0 ,, 0 ,,,,,,

Type RM Length L Ch R = 1 ,7601    ,67.53,67.22,67.01
BEGIN DESCRIPTION:
7601.478--d/s face Willowbend North bridge; channel copied from 7534
END DESCRIPTION:
XS GIS Cut Line= 5
     3090365.113     13807349.25     3092466.091     13806186.67
     3092546.533    13806127.371     3093279.973     13806156.75
     3094761.314    13805486.623
#Sta/Elev= 30
       0   53.36  230.81    55.3  447.68   54.76  525.43   52.39  591.65   55.15
 1098.27   57.03 1271.34   54.72  1485.6    56.6 1629.07   55.71 1662.18   53.96
 1717.06   55.36 1922.78   53.24 2103.63   54.17 2258.14   49.99  2404.6   51.96
 2418.08   47.64  2435.3   38.96    2436   34.93 2454.44   34.88 2455.45   38.92
 2472.93   47.66 2487.42   51.74 3342.51   53.85 3493.43   56.72 3627.56   56.69
 3693.42   53.78 3799.49   57.13 4014.87   54.19  4184.9   57.39 4861.02   56.88
#Mann= 3 , 0 , 0
       0     .15       0  2404.6    .017       0 2487.42     .15       0
#XS Ineff= 2 , 0
       0    2400            2507       0
Permanent Ineff=
       T       T
Bank Sta=2404.6,2487.42
XS Rating Curve= 0
Exp/Cntr=.5,.3

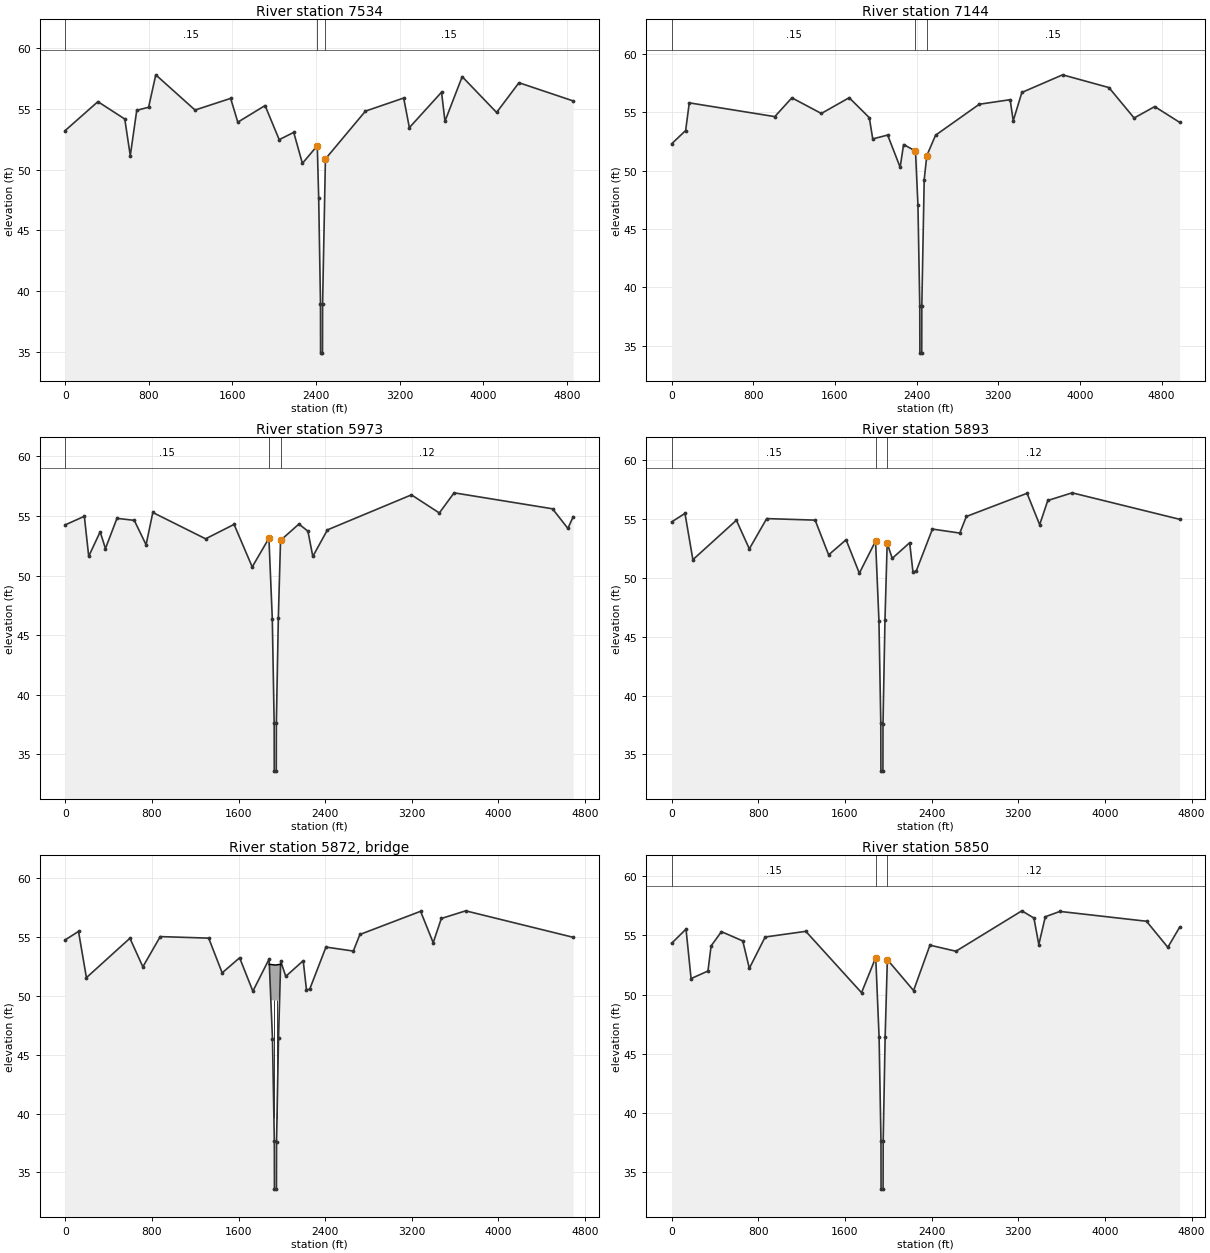
Type RM Length L Ch R = 1 ,7534    ,389.98,390.44,360.9
BEGIN DESCRIPTION:
7534.258--d/s exit Willowbend North bridge; surveyed channel
END DESCRIPTION:
XS GIS Cut Line= 5
     3090404.034    13807404.057     3092505.011    13806241.477
     3092585.453    13806182.177     3093318.893    13806211.557
     3094800.234     13805541.43
#Sta/Elev= 30
       0   53.21  313.02   55.59  570.23   54.16  622.83   51.14   684.8   54.88
  798.27   55.13  866.84    57.8 1242.45    54.9 1583.24   55.86 1651.79    53.9
 1912.59   55.27 2047.96   52.46 2186.88   53.06 2269.83   50.51 2412.27   51.96
 2425.75   47.64 2442.97   38.96 2443.67   34.93 2462.11   34.88 2463.12   38.92
 2490.18   50.87 2873.03   54.81 3239.11   55.89 3293.52   53.45 3601.31   56.37
 3634.24   53.98 3798.87   57.65 4128.14    54.7 4342.16   57.15 4861.02   55.65
#Mann= 3 , 0 , 0
       0     .15       0 2412.27    .017       0 2490.18     .15       0
#XS Ineff= 2 , 0
       0    2408            2513       0
Permanent Ineff=
       T       T
Bank Sta=2412.27,2490.18
XS Rating Curve= 0
Exp/Cntr=.3,.1

Type RM Length L Ch R = 1 ,7144    ,1164.54,1171.21,1115.58
BEGIN DESCRIPTION:
 7143.817--surveyed channel
END DESCRIPTION:
XS GIS Cut Line= 4
     3090602.387    13807629.111     3092736.642    13806555.564
      3092818.93    13806494.722     3095285.154     13806181.69
#Sta/Elev= 30
       0   52.29  137.11   53.43  172.58    55.8 1010.44   54.62 1178.01   56.23
 1466.52   54.89 1739.38   56.24 1936.66   54.53 1970.24   52.71 2116.41   53.04
 2238.89   50.28 2272.47   52.23 2389.05   51.67 2413.24   47.03 2431.05   38.42
 2432.15   34.36 2450.44   34.37  2451.2   38.43  2474.4   49.22 2500.02   51.28
 2586.02   53.03 3014.12   55.68 3316.52   56.07 3346.76   54.26 3431.31   56.69
 3830.61    58.2 4284.23   57.11 4531.53    54.5 4732.79   55.48  4977.4   54.13
#Mann= 3 , 0 , 0
       0     .15       0 2389.05    .017       0 2500.02     .15       0
#XS Ineff= 2 , 0
       0    2380            2527       0
Permanent Ineff=
       T       T
Bank Sta=2389.05,2500.02
XS Rating Curve= 0
Exp/Cntr=.3,.1

Type RM Length L Ch R = 1 ,5973    ,80.21,80.07,80.09
BEGIN DESCRIPTION:
5972.609--u/s approach McDermed bridge; channel copied from 5821
END DESCRIPTION:
XS GIS Cut Line= 6
     3091523.402      13808146.4     3093000.212     13807732.75
     3093302.997     13807563.45      3093382.52      13807504.1
      3093548.94     13807388.55     3096056.206    13807412.203
#Sta/Elev= 30
       0   54.25  176.85   54.97  217.15   51.61  322.88   53.67  371.55   52.26
  477.91    54.8  637.73   54.63  746.77   52.58  809.08   55.29 1296.39   53.08
 1559.18   54.29 1726.57   50.72 1880.87   53.13 1911.97   46.38 1929.23   37.63
 1930.12   33.58  1948.7   33.58 1949.57   37.61 1967.68   46.41 1988.04   52.95
 2157.92   54.32 2240.94   53.72 2285.94    51.6 2420.95   53.83  3196.6   56.77
 3454.04   55.25 3590.34   56.94 4498.95    55.6 4641.05   53.95 4689.76   54.94
#Mann= 3 , 0 , 0
       0     .15       0 1880.87    .017       0 1988.04     .12       0
#XS Ineff= 2 , 0
       0    1870            2016       0
Permanent Ineff=
       T       T
Bank Sta=1880.87,1988.04
XS Rating Curve= 0
Exp/Cntr=.5,.3

Type RM Length L Ch R = 1 ,5893    ,42.12,42.04,42.05
BEGIN DESCRIPTION:
5892.538--u/s face McDermed bridge; channel copied from 5821
END DESCRIPTION:
XS GIS Cut Line= 6
     3091566.984     13808213.57     3093043.794     13807799.92
     3093346.579     13807630.62     3093426.102     13807571.27
     3093592.522     13807455.72     3096099.788    13807479.373
#Sta/Elev= 30
       0   54.76  122.98   55.48  195.99   51.55  597.56    54.9  717.09   52.47
  877.44   55.04 1324.61   54.91 1449.22   51.96 1610.32   53.24 1732.66    50.4
 1882.49   53.13 1913.59   46.38 1930.85   37.63 1931.74   33.58 1950.32   33.58
 1951.19   37.61  1969.3   46.41 1989.66   52.95 2036.26   51.66 2197.36   52.99
 2227.36   50.53 2257.36   50.57 2407.37   54.15 2660.11   53.81 2720.68   55.22
 3280.99   57.19 3397.41   54.52 3472.42   56.58 3697.43   57.23 4689.76   54.98
#Mann= 3 , 0 , 0
       0     .15       0 1882.49    .017       0 1989.66     .12       0
#XS Ineff= 2 , 0
       0    1870            1990       0
Permanent Ineff=
       T       T
Bank Sta=1882.49,1989.66
XS Rating Curve= 0
Exp/Cntr=.5,.3

Type RM Length L Ch R = 3 ,5872    ,,,
BEGIN DESCRIPTION:
McDermed Bridge
END DESCRIPTION:
Bridge Culvert--1,0,-1,-1, 0
Deck Dist Width WeirC Skew NumUp NumDn MinLoCord MaxHiCord MaxSubmerge Is_Ogee
5,32,2.6,0, 7, 7, , , .95, 0, 0,0,,
 1882.83 1898.65 1898.65 1941.03  1983.4  1983.4 1989.83
   52.67   52.67   52.67   52.62   52.68   52.68   52.68
       0       0   49.65    49.6   49.66       0       0
    1884 1899.82 1899.82  1942.2 1984.57 1984.57    1991
   52.67   52.67   52.67   52.62   52.68   52.68   52.68
       0       0   49.65    49.6   49.66       0       0
Pier Skew, UpSta & Num, DnSta & Num=  ,1926.9, 2 ,1928.07, 2 , 0 , 0 , 0 ,,
    1.23    1.23
       0   49.61
    1.23    1.23
       0   49.61
Pier Skew, UpSta & Num, DnSta & Num=  ,1955.15, 2 ,1956.32, 2 , 0 , 0 , 0 ,,
    1.23    1.23
       0   49.61
    1.23    1.23
       0   49.61
BR Coef=-1 , 1 , 1 ,1.05, 0 ,,,.8,-1,1.2,0,
WSPro=,,,, 1 ,,,, 0 ,,,, 0 ,,,,-1 ,-1 ,-1 , 0 , 0 , 0 , 0 , 0
BC Design=,, 0 ,, 0 ,,,,,,

Type RM Length L Ch R = 1 ,5850    ,29.69,29.66,29.66
BEGIN DESCRIPTION:
5850.497--d/s face McDermed bridge; channel copied from 5821
END DESCRIPTION:
XS GIS Cut Line= 6
     3091589.864     13808248.84     3093066.674     13807835.19
     3093369.459     13807665.89     3093448.982     13807606.54
     3093615.402     13807490.99     3096122.668    13807514.643
#Sta/Elev= 30
       0   54.33  132.55   55.53  179.28   51.35  335.05   51.99  364.23   54.11
  459.67   55.31  656.29   54.53  717.13   52.22  863.16   54.86 1238.54   55.34
 1753.01   50.16 1884.06   53.13 1915.16   46.38 1932.42   37.63 1933.31   33.58
 1951.89   33.58 1952.76   37.61 1970.87   46.41 1991.23   52.95 2233.45   50.34
 2384.49   54.17  2624.5   53.66 3232.92   57.07 3344.53   56.46 3389.53   54.22
 3449.53   56.57 3584.54   57.02 4383.83   56.19  4580.7   53.99 4689.76   55.69
#Mann= 3 , 0 , 0
       0     .15       0 1884.06    .017       0 1991.23     .12       0
#XS Ineff= 2 , 0
       0    1880            2000       0
Permanent Ineff=
       T       T
Bank Sta=1884.06,1991.23
XS Rating Curve= 0
Exp/Cntr=.5,.3

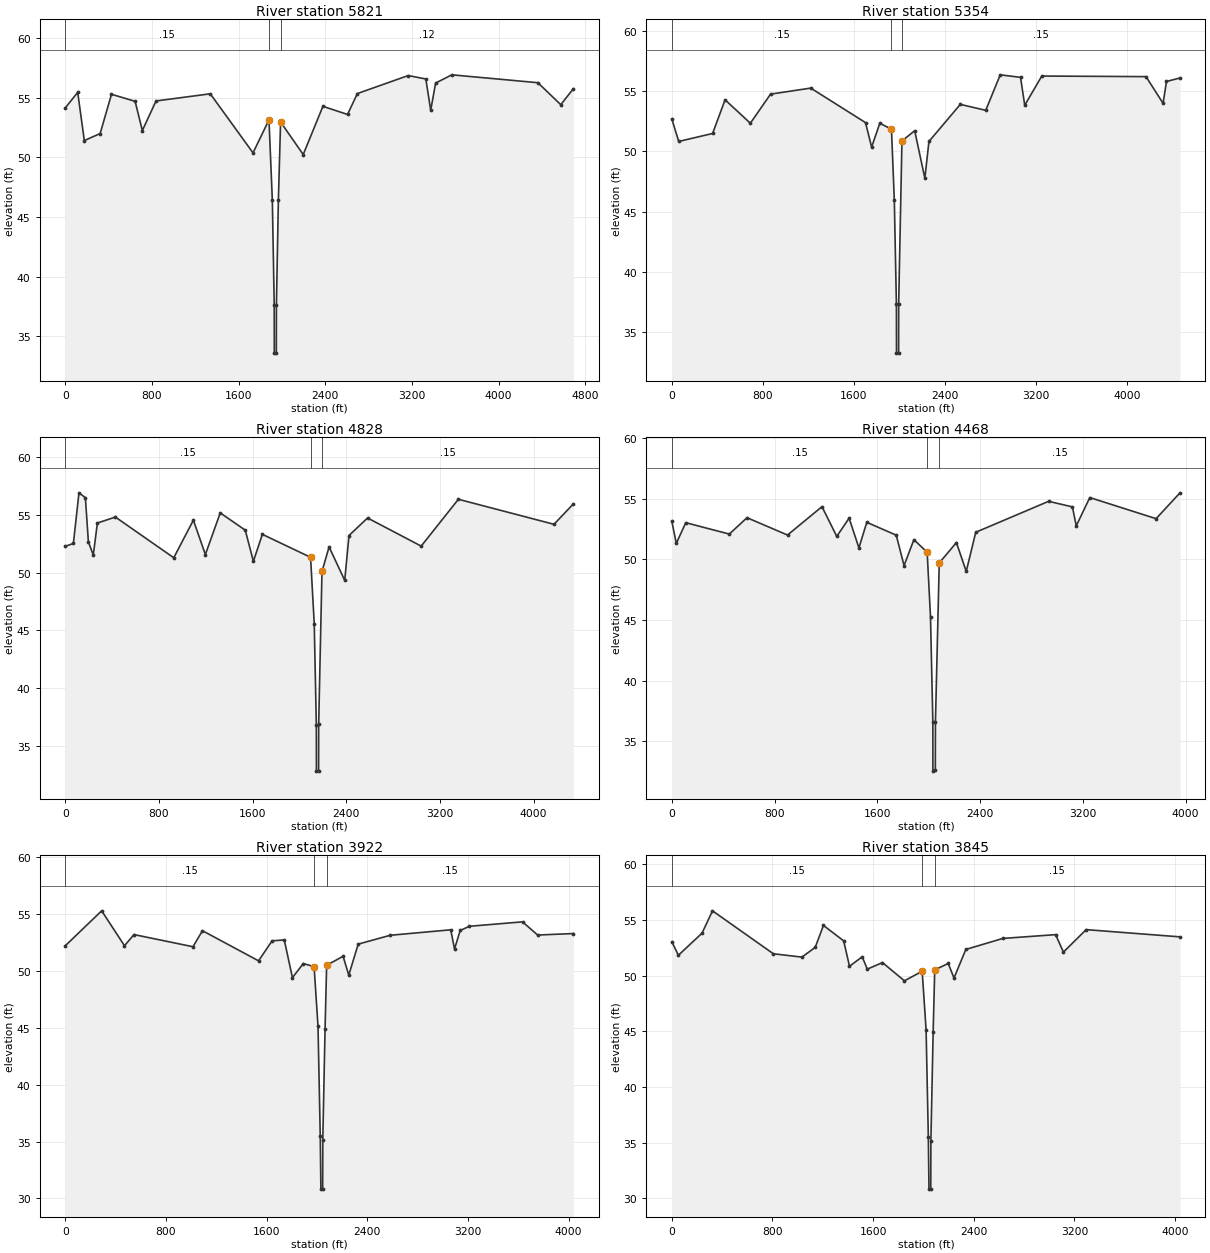
Type RM Length L Ch R = 1 ,5821    ,452.62,466.5,500.24
BEGIN DESCRIPTION:
5820.837--d/s exit McDermed bridge; surveyed channel
END DESCRIPTION:
XS GIS Cut Line= 6
     3091606.147    13808273.619     3093082.957    13807859.968
     3093385.742    13807690.668     3093465.265    13807631.318
     3093631.685    13807515.768     3096138.951    13807539.421
#Sta/Elev= 30
       0   54.12  115.37   55.43  176.43   51.39  322.45   51.98  427.18   55.27
  645.27   54.68  711.85   52.23  838.36   54.71 1338.88   55.31 1733.36   50.36
 1880.55   53.13 1911.65   46.38 1928.91   37.63  1929.8   33.58 1948.38   33.58
 1949.25   37.61 1967.36   46.41 1987.72   52.95  2196.6   50.22 2378.32   54.26
 2605.47   53.58 2696.33   55.33 3165.78   56.84 3328.25   56.55 3373.25   53.93
 3418.25   56.21 3568.26    56.9 4362.12   56.24  4573.3    54.4 4689.76   55.74
#Mann= 3 , 0 , 0
       0     .15       0 1880.55    .017       0 1987.72     .12       0
#XS Ineff= 2 , 0
       0    1870            2000       0
Permanent Ineff=
       T       T
Bank Sta=1880.55,1987.72
XS Rating Curve= 0
Exp/Cntr=.3,.1

Type RM Length L Ch R = 1 ,5354    ,516.84,525.94,531.41
BEGIN DESCRIPTION:
 5354.341--surveyed channel
END DESCRIPTION:
XS GIS Cut Line= 5
     3091792.341    13808540.968     3093661.635    13808064.419
     3093747.893    13808004.393     3094771.119    13807797.931
     3096156.182    13807811.185
#Sta/Elev= 30
       0   52.68   60.55   50.82  358.12   51.48  467.61   54.27  689.64   52.33
  867.03   54.74 1220.05   55.24 1701.12   52.38 1754.69   50.35 1826.78   52.33
 1929.08   51.83 1953.97      46 1972.28   37.34  1973.2   33.28 1991.68    33.3
 1992.32   37.35 2021.08   50.86 2133.06   51.71  2222.2   47.77  2258.2   50.82
 2533.65   53.89 2756.99    53.4 2884.32   56.34 3062.58   56.13  3099.4   53.82
 3249.41   56.24 4164.45   56.19 4314.45   53.98 4344.46   55.79 4463.15   56.08
#Mann= 3 , 0 , 0
       0     .15       0 1929.08    .017       0 2021.08     .15       0
#XS Ineff= 2 , 0
       0    1920            2044       0
Permanent Ineff=
       T       T
Bank Sta=1929.08,2021.08
XS Rating Curve= 0
Exp/Cntr=.3,.1

Type RM Length L Ch R = 1 ,4828    ,354.55,360.49,385.62
BEGIN DESCRIPTION:
 4828.398--surveyed channel
END DESCRIPTION:
XS GIS Cut Line= 5
     3091901.954    13808883.807     3093960.075    13808487.982
     3094060.742    13808434.241     3095331.168    13808082.336
      3096142.99     13808111.75
#Sta/Elev= 30
       0   52.27   69.91   52.52  117.66   56.91   172.4   56.49  198.02   52.66
  239.86   51.52  274.88   54.29  428.62   54.81  927.23   51.28 1094.79   54.54
 1197.28   51.56 1324.38   55.17 1538.23   53.67 1607.23   50.97  1684.1   53.31
 2095.84   51.32 2127.12   45.58 2144.99   36.81 2145.74   32.78 2164.35   32.78
  2165.1   36.83 2193.31   50.09 2253.94   52.22  2387.5   49.32 2424.07   53.21
 2582.52   54.73 3040.61   52.29 3358.39   56.35 4174.98   54.18 4340.57   55.95
#Mann= 3 , 0 , 0
       0     .15       0 2095.84    .017       0 2193.31     .15       0
#XS Ineff= 2 , 0
       0    2085            2207       0
Permanent Ineff=
       T       T
Bank Sta=2095.84,2193.31
XS Rating Curve= 0
Exp/Cntr=.3,.1

Type RM Length L Ch R = 1 ,4468    ,497.1,546.06,567.69
BEGIN DESCRIPTION:
 4467.905--surveyed channel
END DESCRIPTION:
XS GIS Cut Line= 4
     3092223.316    13809160.492     3094173.857    13808777.573
     3094272.975    13808723.755     3096122.564    13808577.123
#Sta/Elev= 30
       0   53.14   34.84   51.32  108.34   53.03  447.57   52.09  585.14   53.44
  900.56   52.01  1168.9   54.35  1283.9    51.9 1380.03    53.4 1456.46   50.95
 1517.61   53.06  1746.9      52 1807.79   49.49 1884.33   51.63 1987.77   50.59
 2013.67   45.25    2032   36.59 2032.44   32.55 2051.21   32.64  2052.1   36.58
  2081.8   49.71 2215.44   51.39 2291.82   49.01 2365.91   52.24 2933.14   54.79
 3118.27   54.33 3148.36   52.77 3253.69    55.1 3769.65   53.36 3955.95   55.49
#Mann= 3 , 0 , 0
       0     .15       0 1987.77    .017       0  2081.8     .15       0
#XS Ineff= 2 , 0
       0    1980            2113       0
Permanent Ineff=
       T       T
Bank Sta=1987.77,2081.8
XS Rating Curve= 0
Exp/Cntr=.3,.1

Type RM Length L Ch R = 1 ,3922    ,72.89,76.62,75.97
BEGIN DESCRIPTION:
3921.847--u/s approach Bellfort bridge; channel copied from 3609
END DESCRIPTION:
XS GIS Cut Line= 4
       3092434.9    13809472.405     3094392.589    13809231.336
     3094507.608    13809242.674     3096456.369     13809299.55
#Sta/Elev= 30
       0   52.22  289.77    55.3  471.13   52.23   546.7   53.21 1015.21   52.14
 1090.78   53.55 1536.27    50.9 1643.92   52.66 1740.65   52.74 1805.39   49.42
 1891.78   50.66 1977.53   50.39 2008.68   45.14 2026.39    35.5 2031.48   30.86
 2045.75   30.81 2046.74   35.14 2064.63   44.91 2077.28   50.51    2208    51.3
    2253   49.64 2328.05   52.37 2583.16   53.15 3063.36   53.63 3093.37   51.94
 3138.39   53.57 3211.37   53.94  3633.6   54.33 3753.65   53.17 4037.64    53.3
#Mann= 3 , 0 , 0
       0     .15       0 1977.53    .017       0 2077.28     .15       0
#XS Ineff= 2 , 0
       0    1966            2094       0
Permanent Ineff=
       T       T
Bank Sta=1977.53,2077.28
XS Rating Curve= 0
Exp/Cntr=.5,.3

Type RM Length L Ch R = 1 ,3845    ,93.87,98.82,101.96
BEGIN DESCRIPTION:
3845.227--u/s face Bellfort bridge;   channel copied from 3609
END DESCRIPTION:
XS GIS Cut Line= 4
       3092431.9    13809555.405     3094389.589    13809304.336
     3094501.591    13809318.279     3096452.869     13809382.07
#Sta/Elev= 30
       0   53.04   52.28   51.83  239.93   53.81  323.23   55.82  807.16   51.96
    1034   51.66 1139.86   52.54 1205.01   54.51 1365.86   53.12 1412.07   50.84
  1513.3   51.69 1553.51   50.58 1674.14   51.17  1848.4   49.53 1989.74   50.39
 2020.89   45.14  2038.6    35.5 2043.69   30.86 2057.96   30.81 2058.95   35.14
 2076.84   44.91 2089.49   50.51 2196.94   51.09 2242.58   49.78 2336.58   52.35
 2631.37   53.34 3050.28   53.68 3112.34   52.11 3293.14   54.13 4038.91   53.48
#Mann= 3 , 0 , 0
       0     .15       0 1989.74    .017       0 2089.49     .15       0
#XS Ineff= 2 , 0
       0    1970            2099       0
Permanent Ineff=
       T       T
Bank Sta=1989.74,2089.49
XS Rating Curve= 0
Exp/Cntr=.5,.3