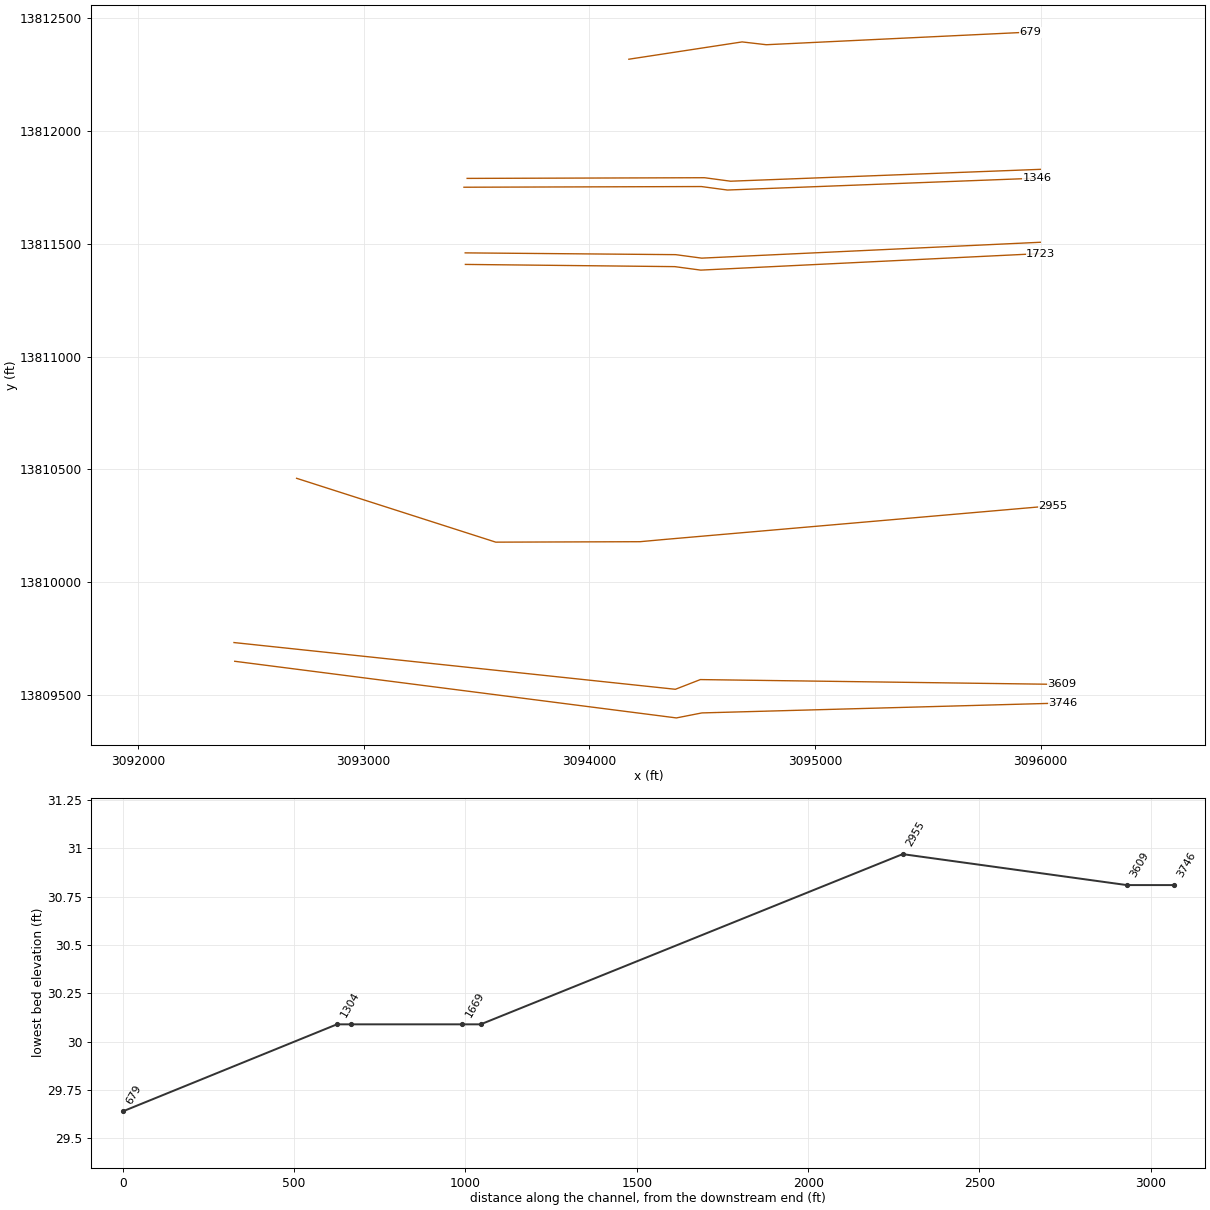
HEC-RAS study D112-00-00.prj: D112-00-00

--- D112-00-00.g05 (geometry) --- (continued)

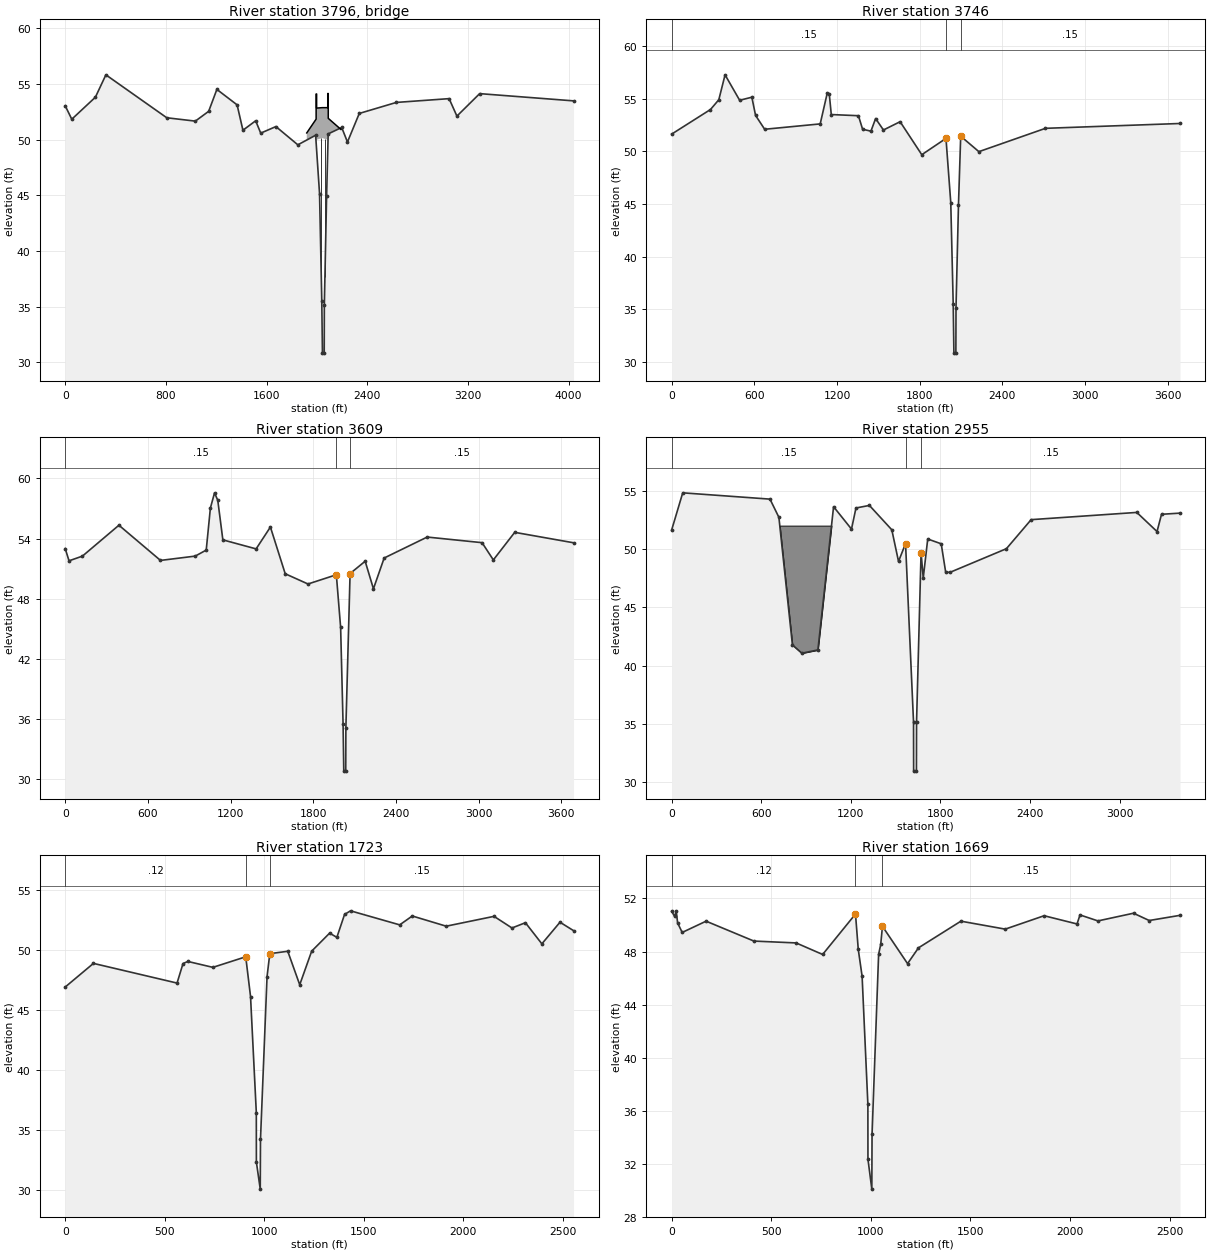
Type RM Length L Ch R = 3 ,3796    ,,,
BEGIN DESCRIPTION:
Bellfort  Bridge  modeled as a single bridge
END DESCRIPTION:
Bridge Culvert--1,0,-1,-1, 0
Deck Dist Width WeirC Skew NumUp NumDn MinLoCord MaxHiCord MaxSubmerge Is_Ogee
6,85,2.6,0, 11, 11, , , .95, 0, 0,0,,
 1919.25 1993.64 1993.64 1997.64 1997.64 2041.83 2086.02 2086.02 2090.02 2090.02
 2191.07
    50.6   51.84    54.1    54.1   52.83   52.87   52.87   54.14   54.14   51.91
   50.91
       0       0       0       0   49.99   50.14   49.99       0       0       0
       0
 1923.71  1998.1  1998.1  2002.1  2002.1 2046.29 2090.48 2090.48 2094.48 2094.48
 2195.53
    50.6   51.84    54.1    54.1   52.83   52.87   52.87   54.14   54.14   51.91
   50.91
       0       0       0       0   49.99   50.14   49.99       0       0       0
       0
Pier Skew, UpSta & Num, DnSta & Num=  ,2034.1, 2 ,2038.56, 2 , 0 , 0 , 0 ,,
    1.35    1.35
       0   50.12
    1.35    1.35
       0   50.12
Pier Skew, UpSta & Num, DnSta & Num=  ,2063.56, 2 ,2068.02, 2 , 0 , 0 , 0 ,,
    1.35    1.35
       0   50.12
    1.35    1.35
       0   50.12
BR Coef=-1 , 1 , 1 ,1.05, 0 ,,,.8,-1,1.2,0,
WSPro=,,,, 1 ,,,, 0 ,,,, 0 ,,,,-1 ,-1 ,-1 , 0 , 0 , 0 , 0 , 0
BC Design=,, 0 ,, 0 ,,,,,,

Type RM Length L Ch R = 1 ,3746    ,125.1,137.4,146.11
BEGIN DESCRIPTION:
3746.412--d/s face Bellfort Bridge;  channel copied from 3609
END DESCRIPTION:
XS GIS Cut Line= 4
       3092428.2    13809649.405     3094385.889    13809398.336
     3094499.013    13809420.518     3096098.344    13809464.409
#Sta/Elev= 30
       0   51.65  281.59   53.99  342.08   54.92  387.45   57.29  493.31   54.87
  581.91   55.16  608.72   53.43  674.78   52.11 1077.85   52.62 1128.47   55.52
 1143.59   55.48 1158.28   53.51 1355.31    53.4 1385.56   52.11 1446.05   51.93
 1479.97   53.13 1536.78   52.04 1657.77   52.83 1815.06   49.69 1990.65   51.24
 2025.35   45.14 2043.06    35.5 2048.15   30.86 2062.42   30.81 2063.41   35.14
  2081.3   44.91 2097.49   51.45 2229.41   49.98 2712.72    52.2 3688.93   52.66
#Mann= 3 , 0 , 0
       0     .15       0 1990.65    .017       0 2097.49     .15       0
#XS Ineff= 2 , 0
       0    1973            2106       0
Permanent Ineff=
       T       T
Bank Sta=1990.65,2097.49
XS Rating Curve= 0
Exp/Cntr=.5,.3

Type RM Length L Ch R = 1 ,3609    ,648.55,654.12,642.56
BEGIN DESCRIPTION:
3609.011--d/s exit Bellfort Bridge;  surveyed channel
END DESCRIPTION:
XS GIS Cut Line= 4
       3092424.9    13809732.405     3094381.389    13809525.278
     3094492.027    13809568.284     3096094.332    13809546.853
#Sta/Elev= 30
       0      53   27.75   51.78  125.04   52.25  389.77   55.33  691.44   51.82
  943.43   52.25 1023.29   52.85 1053.45   57.04 1083.62   58.56  1107.1   57.81
 1143.96   53.87  1385.3   52.97 1489.02   55.15 1596.47   50.49 1761.81   49.47
 1967.42   50.39 1998.57   45.14 2016.28    35.5 2021.37   30.86 2035.64   30.81
 2036.63   35.14 2067.17   50.51  2176.6   51.74 2236.61   48.99 2314.35   52.06
 2626.64   54.15 3024.91   53.59 3106.69   51.87 3261.76   54.62 3688.57   53.58
#Mann= 3 , 0 , 0
       0     .15       0 1967.42    .017       0 2067.17     .15       0
#XS Ineff= 2 , 0
       0    1950            2086       0
Permanent Ineff=
       T       T
Bank Sta=1967.42,2067.17
XS Rating Curve= 0
Exp/Cntr=.3,.1

Type RM Length L Ch R = 1 ,2955    ,1258.24,1231.55,1220.21
BEGIN DESCRIPTION:
2954.888--surveyed channel; blocked obstruction in LOB detention ponds
END DESCRIPTION:
XS GIS Cut Line= 5
     3092702.386    13810460.492     3093585.215     13810177.48
     3094224.516    13810179.441     3094328.053    13810188.936
     3096055.776    13810339.068
#Sta/Elev= 30
       0   51.65   74.04   54.83  658.51   54.29  718.15   52.73  808.72   41.79
  871.73   41.08  979.37   41.36 1084.37   53.64 1204.37   51.72 1234.37   53.53
 1324.37   53.75 1474.37   51.66 1519.37   48.95 1566.39   50.48 1619.92   35.16
 1620.65   30.97 1639.25   30.97 1640.14    35.2 1670.36   49.71 1684.86   47.52
 1714.97   50.87 1805.31   50.46 1835.43   48.01 1865.54   48.02 2241.95   50.04
 2407.57   52.53 3115.23   53.15 3250.74   51.51 3280.85   52.99 3404.59   53.09
#Mann= 3 , 0 , 0
       0     .15       0 1566.39    .017       0 1670.36     .15       0
#XS Ineff= 2 , 0
       0    1558            1678       0
Permanent Ineff=
       T       T
#Block Obstruct= 1 ,-1
  685.77    1084   52.02
Bank Sta=1566.39,1670.36
XS Rating Curve= 0
Exp/Cntr=.3,.1

Type RM Length L Ch R = 1 ,1723    ,54.92,54.64,58.42
BEGIN DESCRIPTION:
1723.339--u/s approach 610;  channel copied from 1346
END DESCRIPTION:
XS GIS Cut Line= 4
     3093450.648    13811408.544     3094378.626     13811398.74
     3094493.983    13811383.287      3096001.38    13811456.751
#Sta/Elev= 30
       0   46.93  141.86    48.9  561.88   47.26  591.88   48.89  616.42   49.06
  741.89   48.57   906.9   49.45  931.01   46.14  960.03   36.47  960.37   32.35
  979.81   30.09     981   34.23 1013.91   47.79 1027.79   49.71 1118.02   49.91
 1178.09   47.12 1238.16   49.92 1328.27   51.42 1364.69   51.07 1403.36   52.98
  1433.4   53.28 1680.43   52.11 1743.58   52.85 1913.96      52 2154.25   52.82
 2244.36   51.85 2311.92   52.29 2394.53   50.53 2485.58   52.33  2553.6   51.63
#Mann= 3 , 0 , 0
       0     .12       0   906.9    .017       0 1027.79     .15       0
#XS Ineff= 2 , 0
       0     846            1055       0
Permanent Ineff=
       T       T
Bank Sta=906.9,1027.79
XS Rating Curve= 0
Exp/Cntr=.5,.3

Type RM Length L Ch R = 1 ,1669    ,312.63,322.97,323.4
BEGIN DESCRIPTION:
1668.701--u/s face 610;  channel copied from 1346
END DESCRIPTION:
XS GIS Cut Line= 4
     3093449.697    13811459.713     3094382.764     13811451.84
     3094498.121    13811436.387     3095998.948    13811506.736
#Sta/Elev= 30
       0   51.03   14.89   50.65    22.8   51.07   29.77   50.16    52.8   49.44
  172.81   50.29  412.82   48.79  624.77   48.65  757.83   47.78  922.84   50.83
  936.77   48.16  956.03   46.14  985.05   36.47  985.39   32.35 1004.83   30.09
 1006.02   34.23 1038.93   47.79 1049.49   48.54 1058.17    49.9 1184.21   47.09
 1239.07   48.28 1452.04   50.29 1674.55   49.69 1869.77    50.7 2034.98   50.08
 2049.96   50.76 2140.06   50.31 2318.57   50.89 2397.34   50.34 2551.96   50.73
#Mann= 3 , 0 , 0
       0     .12       0  922.84    .017       0 1058.17     .15       0
#XS Ineff= 2 , 0
       0     902            1059       0
Permanent Ineff=
       T       T
Bank Sta=922.84,1058.17
XS Rating Curve= 0
Exp/Cntr=.5,.3

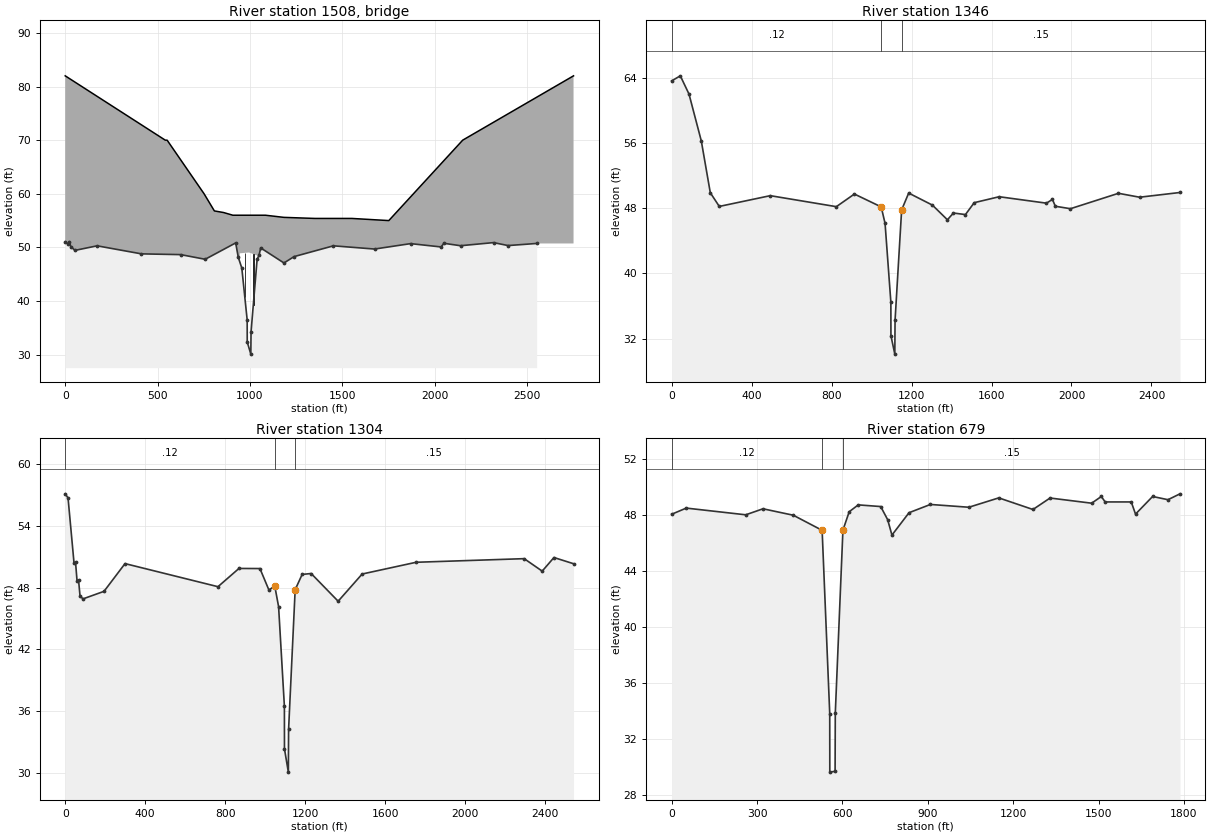
Type RM Length L Ch R = 3 ,1508    ,,,
BEGIN DESCRIPTION:
610 Main Bridge
END DESCRIPTION:
Bridge Culvert--1,0,-1,-1, 0
Deck Dist Width WeirC Skew NumUp NumDn MinLoCord MaxHiCord MaxSubmerge Is_Ogee
11,300,2.6,0, 20, 20, , , .95, 0, 0,0,,
       0  541.75  551.75  751.75  807.55  857.55  907.55  945.14  945.14  995.11
 1045.08 1045.08 1083.95 1133.95 1183.95 1351.75 1551.75 1751.75 2151.75 2751.75
      82      70      70      60    56.8    56.5      56      56      56      56
      56      56      56    55.8    55.6    55.4    55.4      55      70      82
       0       0       0       0       0       0       0       0   48.89   49.05
   48.41       0       0       0       0       0       0       0       0       0
       0  653.19  663.19  863.19  918.99  968.99 1018.99 1056.58 1056.58 1106.55
 1156.52 1156.52 1195.39 1245.39 1295.39 1463.19 1663.19 1863.19 2263.19 2863.19
      82      70      70      60    56.8    56.5      56      56      56      56
      56      56      56    55.8    55.6    55.4    55.4      55      70      82
       0       0       0       0       0       0       0       0   48.89   49.05
   48.41       0       0       0       0       0       0       0       0       0
Pier Skew, UpSta & Num, DnSta & Num=  ,972.11, 2 ,1083.55, 2 , 0 , 0 , 0 ,,
    2.58    2.58
       0      50
    2.58    2.58
       0      50
Pier Skew, UpSta & Num, DnSta & Num=  ,1018.11, 2 ,1129.55, 2 , 0 , 0 , 0 ,,
    2.58    2.58
       0      50
    2.58    2.58
       0      50
BR Coef=-1 , 1 , 1 ,1.05, 0 ,,,.8,-1,1.2,0,
WSPro=,,,, 1 ,,,, 0 ,,,, 0 ,,,,-1 ,-1 ,-1 , 0 , 0 , 0 , 0 , 0
BC Design=,, 0 ,, 0 ,,,,,,

Type RM Length L Ch R = 1 ,1346    ,39.07,41.74,41.39
BEGIN DESCRIPTION:
1345.730--d/s face 610;  surveyed channel
END DESCRIPTION:
XS GIS Cut Line= 4
      3093444.29     13811750.72     3094496.749    13811753.726
     3094612.105    13811738.273     3095985.119     13811790.87
#Sta/Elev= 30
       0   63.63   43.21   64.25   86.68   62.01  148.21   56.26  193.21    49.9
  238.21   48.22  493.21   49.54  823.79   48.19  914.04   49.74 1048.21   48.16
 1067.47   46.14 1096.49   36.47 1096.83   32.35 1116.27   30.09 1117.46   34.23
 1150.37   47.79 1185.67   49.86 1304.34   48.38  1379.4   46.58 1409.42   47.41
 1469.47   47.22 1513.46   48.68 1638.33   49.41 1874.76   48.62 1904.78   49.08
 1919.29   48.24 1994.85   47.94 2235.03   49.83 2340.74   49.35 2542.87   49.93
#Mann= 3 , 0 , 0
       0     .12       0 1048.21    .017       0 1150.37     .15       0
#XS Ineff= 2 , 0
       0    1040            1188       0
Permanent Ineff=
       T       T
Bank Sta=1048.21,1150.37
XS Rating Curve= 0
Exp/Cntr=.5,.3

Type RM Length L Ch R = 1 ,1304    ,580.62,624.91,644.18
BEGIN DESCRIPTION:
1303.988--d/s exit 610;  channel copied from 1346
END DESCRIPTION:
XS GIS Cut Line= 4
     3093458.305    13811789.834     3094510.764     13811792.84
     3094626.121    13811777.387     3095999.135    13811829.983
#Sta/Elev= 30
       0   57.09    14.2   56.69    44.2   50.36   51.68   50.46    59.2   48.65
   66.72   48.73    74.2   47.17    89.2    46.9   194.2   47.63   299.2   50.32
   764.2   48.08   869.2   49.85   974.2   49.84  1019.2   47.75 1048.21   48.16
 1067.47   46.14 1096.49   36.47 1096.83   32.35 1116.27   30.09 1117.46   34.23
 1150.37   47.79 1185.24   49.27 1230.27   49.36 1365.37   46.67 1485.46   49.31
 1755.66   50.45 2296.06    50.8 2386.12   49.59  2444.9   50.91 2542.87   50.31
#Mann= 3 , 0 , 0
       0     .12       0 1048.21    .017       0 1150.37     .15       0
#XS Ineff= 2 , 0
       0    1039            1200       0
Permanent Ineff=
       T       T
Bank Sta=1048.21,1150.37
XS Rating Curve= 0
Exp/Cntr=.3,.1

Type RM Length L Ch R = 1 ,679     ,112.16,679.08,388.04
BEGIN DESCRIPTION:
 679.078--surveyed channel
END DESCRIPTION:
XS GIS Cut Line= 4
     3094175.188    13812318.115     3094677.191    13812394.829
     3094784.424    13812382.366     3095953.604     13812438.42
#Sta/Elev= 30
       0   48.08   51.26   48.52   260.3   48.04     321   48.47  427.39   48.01
  528.72   46.93  555.43   33.83  555.69   29.64  574.27    29.7  574.99   33.85
   601.8   46.94  623.87   48.26  655.68   48.75  734.55   48.63  759.03   47.69
  774.04   46.59  834.11   48.19   909.2   48.78 1044.35   48.58 1149.47   49.25
 1269.61   48.42 1329.68   49.24  1475.9   48.87 1509.89   49.35 1523.22   48.96
 1615.01   48.96 1630.03   48.09 1690.09   49.35 1744.05   49.12 1786.31   49.54
#Mann= 3 , 0 , 0
       0     .12       0  528.72    .017       0   601.8     .15       0
#XS Ineff= 2 , 0
       0     250             640       0
Permanent Ineff=
       T       T
Bank Sta=528.72,601.8
XS Rating Curve= 0
Exp/Cntr=.3,.1

Chan Stop Cuts=-1